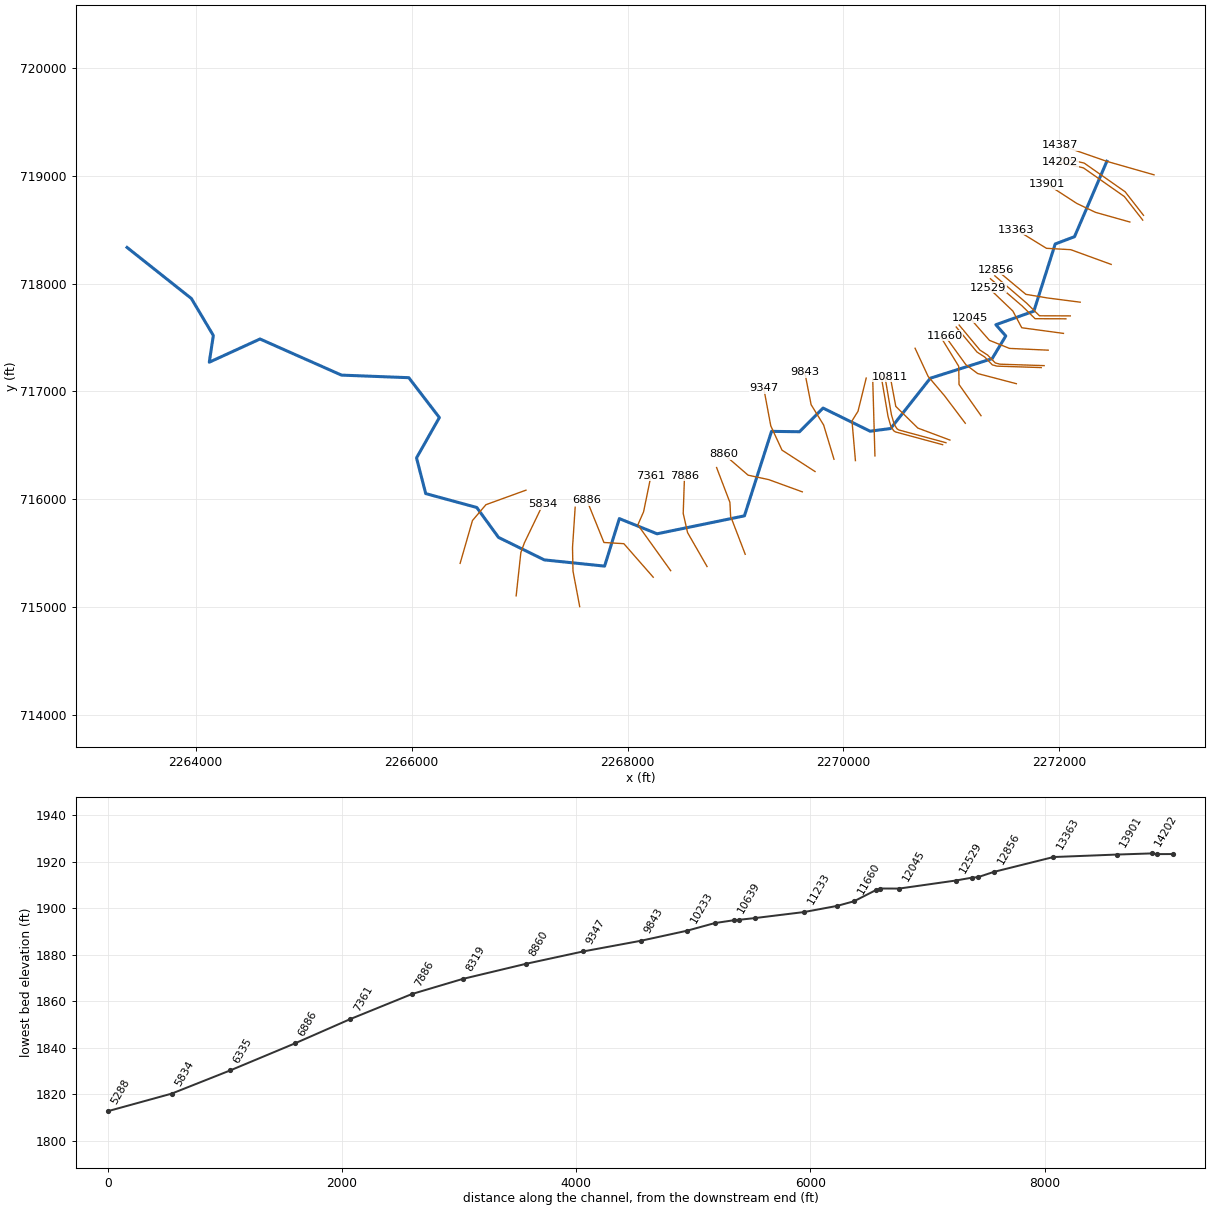
--- BEAVCK2.prj (project) ---

Proj Title=BEAVCK2
Current Plan=p01
Default Exp/Contr=0,0
English Units
Geom File=g01
Flow File=f01
Plan File=p01
BEGIN DESCRIPTION:
----------MODEL BY WOOD PLC 2022----------
AFH study
Randolph County, WV
HEC-RAS Version: RAS 6.2
Vertical Datum: NAVD88
Projection: NAD 1983 StatePlane West Virginia S FIPS 4702 (US Feet)
Terrain: 1-meter LIDAR (FEMA Region III 3DEP collected 2016-2018)
Land Use: 2019 NLCD
Hydrologic Method:
WV SIR2010-5033 regression equations
Additional Model Notes:
Downstream boundary condition starts outside of the county boundary (Barbour County)
END DESCRIPTION:
DSS Export Rating Curves= 0
DSS Export Rating Curve Sorted= 0
DSS Export Volume Flow Curves= 0
DXF OffsetX= 0
DXF OffsetY= 0
DXF ScaleX= 0
DXF ScaleY= 0

--- BEAVCK2.p01 (plan) ---

Plan Title=Floodplain
Program Version=6.20
Short Identifier=Floodplain
Geom File=g01
Flow File=f01
Subcritical Flow
K Sum by GR= 0
Std Step Tol= 0.01
Critical Tol= 0.01
Num of Std Step Trials= 20
Max Error Tol= 0.3
Flow Tol Ratio= 0.001
Split Flow NTrial= 30
Split Flow Tol= 0.02
Split Flow Ratio= 0.02
Log Output Level= 0
Friction Slope Method= 1
Unsteady Friction Slope Method= 2
Unsteady Bridges Friction Slope Method= 1
Parabolic Critical Depth
Global Vel Dist= 0 , 0 , 0
Global Log Level= 0
CheckData=True
Encroach Param=-1 ,0,0, 0
Mapping Interval=1HOUR
Computation Time Step Use Courant=        0
Computation Time Step Use Time Series=    0
Computation Time Step Count To Double=0
Computation Time Step Max Doubling=0
Computation Time Step Max Halving=0
Computation Time Step Residence Courant=0
Run HTab= 0
Run UNet= 0
Run Sediment= 0
Run PostProcess= 0
Run WQNet= 0
Run RASMapper=-1
UNET Theta= 0
UNET Theta Warmup= 0
UNET ZTol= 0
UNET ZSATol= 0
UNET MxIter= 0
UNET Max Iter WO Improvement= 0
UNET MaxInSteps= 0
UNET DtIC= 0
UNET DtMin= 0
UNET MaxCRTS= 0
UNET WFStab= 0
UNET SFStab= 0
UNET WFX= 1
UNET SFX= 1
UNET Gravity=32.174
UNET 1D Methodology=Finite Difference
UNET DSS MLevel= 1
UNET Pardiso=0
UNET DZMax Abort= 0
UNET Use Existing IB Tables= 0
UNET Froude Reduction=False
UNET Froude Limit= 0
UNET Froude Power= 0
UNET D1 Cores= 0
UNET WindReference=Eulerian
UNET WindDragFormulation=Hsu (1988)
UNET D2 Coriolis=0
UNET D2 Cores= 0
UNET D2 Theta= 1
UNET D2 Theta Warmup= 1
UNET D2 Z Tol= 0.01
UNET D2 Volume Tol= 0.01
UNET D2 Max Iterations= 20
UNET D2 Equation= 0
UNET D2 RampUpFraction=0.1
UNET D2 TimeSlices= 1
UNET D2 Turbulence Formulation=Non-Conservative (original)
UNET D2 Eddy Viscosity=0.3
UNET D2 Transverse Eddy Viscosity=0.1
UNET D2 Smagorinsky Mixing=0
UNET D2 BCVolumeCheck=0
UNET D2 Cores=0
UNET D2 SolverType=PARDISO (Direct)
UNET D2 Minimum Iterations= 2147483647
UNET D2 Maximum Iterations= 2147483647
UNET D2 Restart Number= 10
UNET D2 Relaxation Coeff=1.3
UNET D2 SOR Precondition Iterations= 10
UNET D2 ILUT Maximum Fill= 8
UNET D2 ILUT Tolerance=1E-08
UNET D1D2 MaxIter= 0
UNET D1D2 ZTol=0.01
UNET D1D2 QTol=0.1
UNET D1D2 MinQTol=1
Write IC File= 0
Write IC File at Fixed DateTime=0
Write IC File at Sim End=0
Echo Input=False
Echo Parameters=False
Echo Output=False
Write Detailed= 0
HDF Write Warmup=0
HDF Write Time Slices=0
HDF Flush=0
HDF Compression= 1
HDF Chunk Size= 1
HDF Spatial Parts= 1
HDF Use Max Rows=0
HDF Fixed Rows= 1
Calibration Method= 0
Calibration Iterations= 20
Calibration Max Change=0.05
Calibration Tolerance=0.2
Calibration Maximum=1.5
Calibration Minimum=0.5
Calibration Optimization Method= 1
WQ AD Non Conservative
WQ ULTIMATE=-1
WQ Max Comp Step=1HOUR
WQ Output Interval=15MIN
WQ Output Selected Increments= 0
WQ Output face flow=0
WQ Output face velocity=0
WQ Output face area=0
WQ Output face dispersion=0
WQ Output cell volume=0
WQ Output cell surface area=0
WQ Output cell continuity=0
WQ Output cumulative cell continuity=0
WQ Output face conc=0
WQ Output face dconc_dx=0
WQ Output face courant=0
WQ Output face peclet=0
WQ Output face adv mass=0
WQ Output face disp mass=0
WQ Output cell mass=0
WQ Output cell source sink temp=0
WQ Output nsm pathways=0
WQ Output nsm derived pathways=0
WQ Create Restart=0
WQ Fixed Restart=0
WQ System Summary=0
WQ Write To DSS=0
Sorting and Armoring Iterations= 10
XS Update Threshold= 0.02
Bed Roughness Predictor= 0
Hydraulics Update Threshold= 0.02
Energy Slope Method= 1
Volume Change Method= 1
Sediment Retention Method= 0
Sediment TS Multiplier= 1
Warm Up Method= 0
XS Weighting Method= 0
Number of US Weighted Cross Sections= 1
Number of DS Weighted Cross Sections= 1
Upstream XS Weight=0
Main XS Weight=1
Downstream XS Weight=0
Number of DS XS's Weighted with US Boundary= 1
Upstream Boundary Weight= 1
Weight of XSs Associated with US Boundary= 0
Number of US XS's Weighted with DS Boundary= 1
Downstream Boundary Weight= 0.5
Weight of XSs Associated with DS Boundary= 0.5
Percentile Method= 0
Sediment Output Level= 3
Mass or Volume Output= 0
Output Increment Type= 1
Profile and TS Output Increment= 1
Transport Output Increment 1
XS Output Flag= 0
XS Output Increment= 10
Read HDF5 Sediment Hotstart= 0
Sediment Hotstart Type= 0
Write Gradation File= 0
Read Gradation Hotstart= 0
Write HDF5 File= 1
Write Binary Output= 1
Write DSS Sediment File= 0
DSS Sediment Output Type= 1
SV Curve= 0
Specific Gage Flag= 0
Subcell Erosion Methods= 0
Subcell Deposition Methods= 0
Advection Scheme= 1
Matrix Solver= 0
Implicit Weighting Factor= 1
Maximum Outer Loop Convergence Iterations= 5
Convergence Maximum Absolute= 0.001
Convergence RMSE= 0.0001
Grain Fractions Max Abs Error= 0.001
Max Subgrid Regions= 1
Max Subgrid Length Scale= 3.402823E+38
Initial Layer Thickness= 3.402823E+38
Min Layer Thickness= 3.402823E+38
Max Layer Thickness= 3.402823E+38
Number of Layers= 5

--- BEAVCK2.f01 (steady flow) ---

Flow Title=Flow
Program Version=6.20
Number of Profiles= 1
Profile Names=P100yr
River Rch & RM=BEAVCK2,Main,14387
    1430
River Rch & RM=BEAVCK2,Main,8860
    1600
Boundary for River Rch & Prof#=BEAVCK2,Main            , 1
Up Type= 0
Dn Type= 3
Dn Slope=0.00784
DSS Import GetInterval= 0
DSS Import GetPeak= 0
DSS Import FillOption= 0

--- BEAVCK2.g01 (geometry) ---

Geom Title=Geometry
Program Version=6.20

River Reach=BEAVCK2         ,Main
Reach XY= 30
       2272439.3      719132.1482272139.39257723718433.630615182
2271960.76176412718366.103981855      2271763.06      717744.058
 2271411.3053638717618.226999771     2271503.026      717514.419
     2271376.772      717304.202     2270804.122      717122.909
2270436.79381833716657.2404542962270246.40054536  716632.3481633
2269810.96702513716846.615247807     2269592.759       716627.34
     2269333.688      716630.881     2269082.666      715848.352
     2268273.923      715682.291     2267924.464      715822.771
2267787.93624173715382.929429293     2267229.682      715440.586
     2266805.371      715648.893     2266604.149      715925.864
     2266131.562      716054.5542266046.15937011716384.877542191
     2266257.717      716758.705     2265974.738      717127.823
     2265351.009      717151.729 2264597.0047435717486.151557624
      2264127.14      717271.2292264164.59374953717518.697865277
     2263961.198      717861.144     2263365.296      718334.054

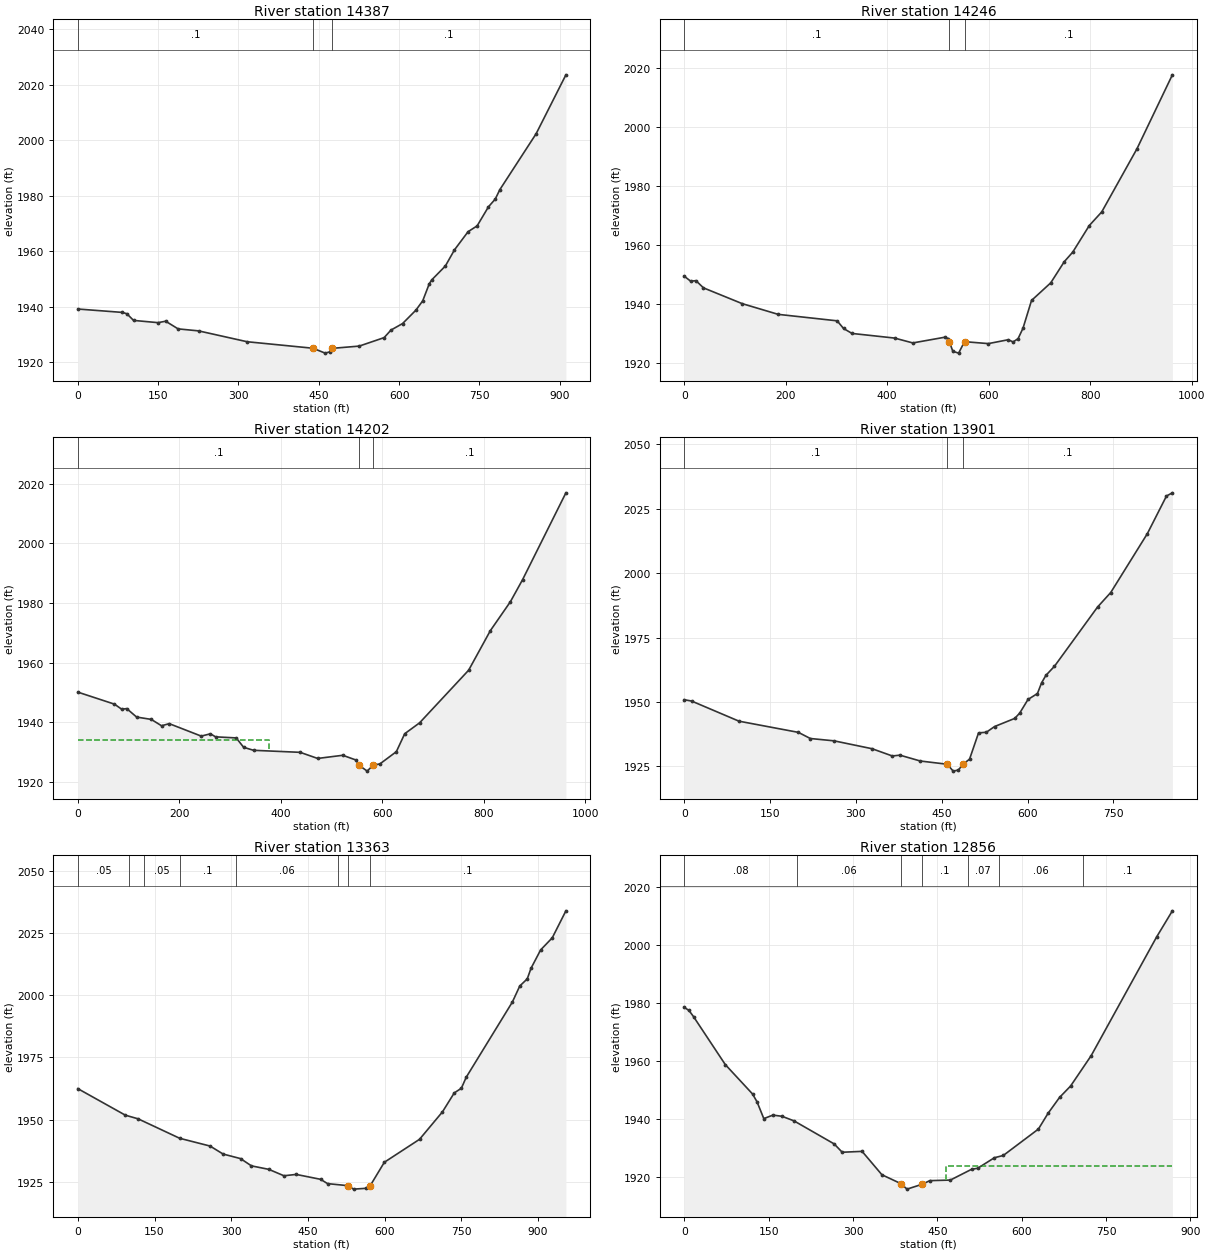
Type RM Length L Ch R = 1 ,14387   ,145.6,141.5,137
XS GIS Cut Line= 3
     2272876.241      719006.4952272438.96309543 719131.24645935
     2272007.677      719281.553
#Sta/Elev= 30
       0 1939.25    83.3 1938.03    91.6 1937.54   104.1 1935.15   149.8 1934.34
     164 1934.86   187.3  1932.1   225.5 1931.38   316.2 1927.47   439.1 1925.13
   461.9 1923.37   470.4 1923.82   474.6 1925.08   525.5  1925.9     572 1928.95
   584.8 1931.67   606.5 1934.02   631.4 1938.85   644.1  1942.2   656.3 1948.33
     661 1949.75   686.4 1954.74   703.4 1960.55   728.8 1967.09   745.7 1969.18
   766.9 1976.05   779.6 1978.84   788.1 1982.22   855.9 2002.36   911.5 2023.56
#Mann= 3 ,-1,0
       0      .1       0   439.1    .045       0   474.6      .1       0
Bank Sta=439.1,474.6
XS Rating Curve= 0 ,0
Exp/Cntr=0.3,0.1

Type RM Length L Ch R = 1 ,14246   ,42.3,43.2,41.6
XS GIS Cut Line= 4
2272778.58580874718631.3487300612272608.33942383718849.476910738
2272229.27520741719115.087872208 2272012.6100816719165.363757754
#Sta/Elev= 30
       0 1949.45    12.5 1947.77      23 1947.94    37.8  1945.5   114.4 1940.13
     185 1936.51   301.3 1934.31   313.9 1931.71   330.6 1930.03   414.5 1928.46
   450.4 1926.81   513.2 1928.74   520.1 1928.31  522.38 1927.24   529.3 1923.97
   540.7 1923.35   552.3 1927.24   599.3 1926.58   638.6  1927.9   648.1 1927.15
   657.9 1928.26   667.6 1931.81   684.4 1941.23   722.3 1947.21   748.9 1954.38
   765.6 1957.62   798.2 1966.64   822.8 1971.28   892.2  1992.7     962  2017.8
#Mann= 3 ,-1,0
       0      .1       0  522.38    .045       0   552.3      .1       0
Bank Sta=522.38,552.3
XS Rating Curve= 0 ,0
Exp/Cntr(USF)=0,0
Exp/Cntr=0.3,0.1

Type RM Length L Ch R = 1 ,14202   ,297.8,301.2,302.5
XS GIS Cut Line= 4
2272771.47004187718587.1245714792272601.22365696718805.252752155
2272222.15944054719070.8637136262272005.49431473719121.139599172
#Sta/Elev= 30
       0 1950.13    72.2  1946.1    86.5  1944.4    96.4 1944.61   115.9 1941.77
   144.7 1940.99     165 1938.86   180.2 1939.56   243.2 1935.39   261.4 1936.16
   271.5 1935.14   312.2 1934.78   326.8 1931.64   346.3 1930.63   438.2 1929.95
   472.7  1927.9   522.2 1928.96   548.4 1927.36   554.61925.589   570.3 1923.65
  581.89 1925.62   595.5 1926.08   627.8 1930.17   644.3 1936.19   673.6 1939.83
   770.3 1957.48   813.1 1970.74   852.5 1980.41   876.5 1987.79     962 2016.93
#Mann= 3 ,-1,0
       0      .1       0   554.6    .045       0  581.89      .1       0
#XS Ineff= 2 , 0
          377.24    1934
Permanent Ineff=
       F       F
Bank Sta=554.6,581.89
XS Rating Curve= 0 ,0
Exp/Cntr(USF)=0,0
Exp/Cntr=0.3,0.1

Type RM Length L Ch R = 1 ,13901   ,529.4,538.1,546.5
XS GIS Cut Line= 4
2272652.15391712718569.5336278742272333.28421291718659.249227689
2272160.54458353718741.8086247012271883.58024695718921.494858928
#Sta/Elev= 30
       0 1950.85    12.7 1950.35    95.6 1942.53   199.4 1938.19   220.2 1935.81
   261.8  1934.9   328.2 1931.84   363.5 1929.03   376.8 1929.35   412.3 1927.08
   459.5 1925.82   469.9 1923.15   478.8 1923.57   487.6 1925.91   498.5 1927.81
   514.2 1937.99   527.9 1938.24   542.2 1940.45   577.5 1943.61   586.1 1945.66
   600.6 1950.95   617.1 1953.26   624.4 1957.42   631.8 1960.28   646.9 1963.85
   722.1 1986.81   745.2 1992.46   809.2 2015.31   842.6 2029.91   852.9 2031.14
#Mann= 3 ,-1,0
       0      .1       0   459.5    .045       0   487.6      .1       0
Bank Sta=459.5,487.6
XS Rating Curve= 0 ,0
Exp/Cntr=0.3,0.1

Type RM Length L Ch R = 1 ,13363   ,506.8,507.3,498.2
XS GIS Cut Line= 4
2272479.18269844718176.9980635272272104.79600703 718313.34556575
2271879.78736506718325.8938571392271598.14715876718499.175603209
#Sta/Elev= 30
       0 1962.47      93  1951.8   117.9 1950.34   199.2 1942.52   258.6  1939.4
   284.2 1936.18   318.2 1934.36   339.5 1931.44   373.6 1930.03   403.1 1927.46
   427.1    1928   474.8 1926.03   488.4  1924.3   527.61923.497   539.3 1922.09
   563.3 1922.41  571.871923.496   599.4 1932.88   668.2  1942.1   713.1 1953.14
   736.1 1960.74   750.1 1962.64   759.5 1967.03   849.8 1997.27   864.3 2003.72
   878.9 2006.58   886.3 2010.85   905.1 2018.22   927.8 2023.07   954.5 2033.92
#Mann= 8 ,-1,0
       0     .05       0     100      .1       0     130     .05       0
     200      .1       0     310     .06       0  508.44      .1       0
   527.6    .045       0  571.87      .1       0
Bank Sta=527.6,571.87
XS Rating Curve= 0 ,0
Exp/Cntr=0.3,0.1

Type RM Length L Ch R = 1 ,12856   ,144.7,137.1,130.4
XS GIS Cut Line= 4
2272192.45332973717827.0697631612271890.92740747717865.929908141
2271688.80390996717899.8060328722271413.15974245718129.633648484
#Sta/Elev= 30
       0 1978.54     8.3 1977.48    16.4 1975.35    72.9 1958.77   121.3 1948.62
   129.3 1945.92   141.4 1940.09   157.6 1941.31   173.8 1940.89   195.1 1939.31
   266.5 1931.35   280.8 1928.47   316.2 1928.77   351.4 1920.69   384.91917.643
   396.1 1915.72     4231917.402   436.6 1918.65   473.1 1918.85   511.1  1922.6
   521.7 1922.93   551.4 1926.57   567.2 1927.35   629.7 1936.48   646.7 1941.88
   667.3 1947.42   686.9 1951.35   723.5 1961.85   839.8 2002.85   867.9 2011.91
#Mann= 7 ,-1,0
       0     .08       0     200     .06       0   384.9    .045       0
     423      .1       0  504.02     .07       0  558.96     .06       0
  708.96      .1       0
#XS Ineff= 2 , 0
                          464.65          1923.8
Permanent Ineff=
       F       F
Bank Sta=384.9,423
XS Rating Curve= 0 ,0
Exp/Cntr=0.3,0.1

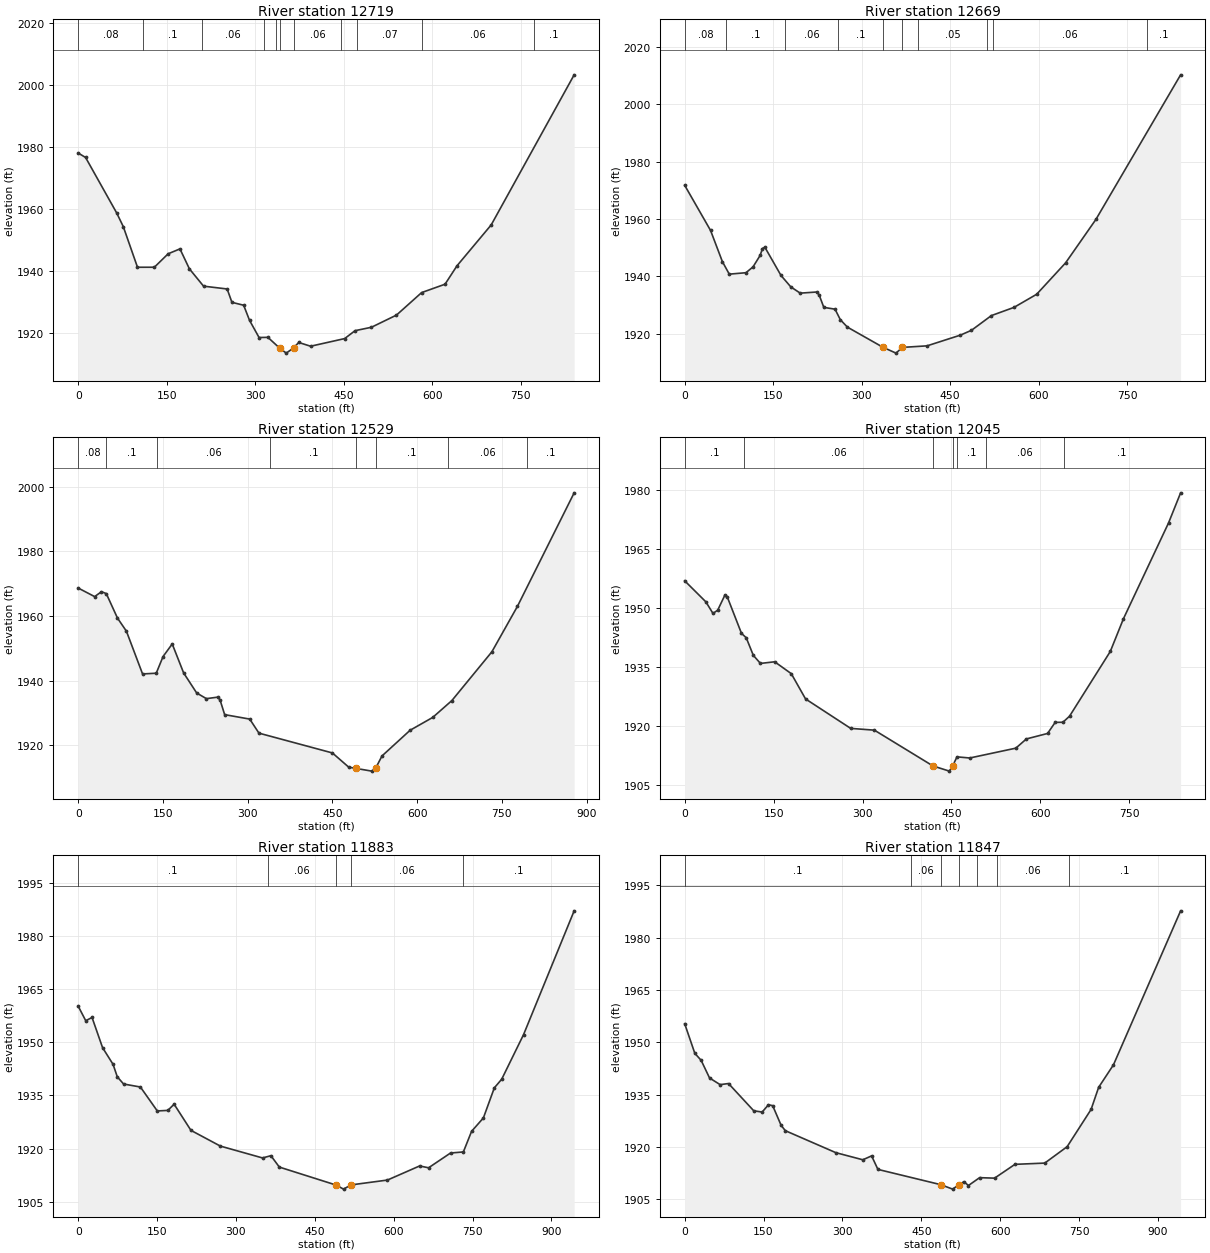
Type RM Length L Ch R = 1 ,12719   ,48.9,49.6,51.4
XS GIS Cut Line= 4
2272100.70760872717700.1599607732271815.16326361717701.183849706
2271695.64018003717818.564014891 2271401.5627062 718071.25022817
#Sta/Elev= 30
       0 1978.11    12.5 1976.68    65.3 1958.72    76.5 1954.29   100.5 1941.19
   129.1  1941.2   152.5 1945.55   172.5 1947.13   188.5 1940.68   212.5 1935.08
   252.5 1934.17   260.6 1929.85   280.5 1928.91   290.5 1924.01   306.6 1918.48
   321.6 1918.53   341.4 1915.07   352.7 1913.43   365.5 1915.17   373.8 1916.88
     394 1915.66   451.7 1918.13   469.4 1920.69   497.1 1921.79   539.6 1925.73
   582.2    1933   621.9 1935.71   642.2 1941.67   700.2 1954.89   840.8  2003.4
#Mann= 11 ,-1,0
       0     .08       0     110      .1       0     210     .06       0
  315.55      .1       0  335.55     .06       0   341.4    .045       0
   365.5     .06       0  445.55     .05       0  473.07     .07       0
  583.07     .06       0  773.07      .1       0
Bank Sta=341.4,365.5
XS Rating Curve= 0 ,0
Exp/Cntr=0.3,0.1

Type RM Length L Ch R = 1 ,12669   ,138.9,139.9,130.3
XS GIS Cut Line= 4
2272060.03156132 717673.18894677 2271774.4872162717674.212835703
2271654.96413263717791.5930008882271360.88665879718044.279214167
#Sta/Elev= 30
       0  1971.8    43.9 1956.03    63.9 1945.17    75.6 1940.79   103.9 1941.29
   115.9 1943.33   127.9 1947.32   131.9 1949.73   135.9  1950.2   163.3 1940.33
   179.9 1936.35   195.9 1934.16   223.9 1934.56   227.9 1933.56   235.9 1929.19
   254.9 1928.57   263.9 1924.89   275.9  1922.3  336.561915.227   358.3 1913.23
  368.991915.227   410.9 1915.77   467.3  1919.5   486.2 1921.19     520 1926.33
   558.3 1929.19   596.7 1933.76   645.8 1944.73   697.3 1959.92   840.8 2010.34
#Mann= 10 ,-1,0
       0     .08       0      70      .1       0     170     .06       0
     260      .1       0  336.56    .045       0  368.99     .06       0
  395.55     .05       0  513.07     .07       0  523.07     .06       0
  783.07      .1       0
Bank Sta=336.56,368.99
XS Rating Curve= 0 ,0
Exp/Cntr=0.3,0.1

Type RM Length L Ch R = 1 ,12529   ,456.5,484.4,486.2
XS GIS Cut Line= 4
2272037.05026452 717538.131015742271651.02146793717590.352915542
2271568.88837559717744.7266424622271342.35014129717961.293572973
#Sta/Elev= 30
       0 1968.66    29.1 1966.01    41.2 1967.53    49.7 1966.94    69.5 1959.36
    85.3 1955.31   113.9 1942.07   138.1 1942.29   150.2 1947.46   166.4 1951.35
   186.6 1942.38   209.7 1936.17   226.9 1934.42   247.1 1934.89   251.1 1933.99
   259.2 1929.47   303.6 1928.09   319.9 1923.74   449.9 1917.61   478.8 1913.21
   492.4  1912.8   519.6 1911.98  526.29 1912.83   537.7 1916.68   587.5 1924.64
   627.5 1928.61   661.4 1933.83   732.2 1948.93   777.4 1962.99   877.8 1998.14
#Mann= 8 ,-1,0
       0     .08       0      50      .1       0     140     .06       0
     340      .1       0   492.4    .045       0  526.29      .1       0
  654.41     .06       0  794.41      .1       0
Bank Sta=492.4,526.29
XS Rating Curve= 0 ,0
Exp/Cntr(USF)=0,0
Exp/Cntr=0.3,0.1

Type RM Length L Ch R = 1 ,12045   ,169.9,161.8,155.4
XS GIS Cut Line= 4
2271895.83285896717382.6905769182271537.31340348717399.095015451
2271351.61332715717473.8155449612271168.64953136717682.306844998
#Sta/Elev= 30
       0 1956.92    35.7 1951.57    47.7 1948.63    55.7 1949.44    67.7 1953.24
    71.7 1952.88    95.8 1943.55   103.8 1942.44   115.8 1937.95   127.8  1935.9
   151.8 1936.32   179.8  1933.3   203.9 1926.87     280 1919.38     320 1918.93
   418.71909.835   446.4 1908.51  452.03 1909.85   459.3 1912.14   480.8 1911.85
   558.5 1914.35   576.4  1916.7   612.1 1918.09   624.9 1920.91     638 1920.94
   649.2 1922.49   717.9 1938.95   740.1 1947.28   816.1 1971.62   836.5 1979.29
#Mann= 7 ,-1,0
       0      .1       0     100     .06       0   418.7    .045       0
  452.03     .06       0  458.89      .1       0  508.89     .06       0
  639.06      .1       0
Bank Sta=418.7,452.03
XS Rating Curve= 0 ,0
Exp/Cntr(USF)=0,0
Exp/Cntr=0.3,0.1

Type RM Length L Ch R = 1 ,11883   ,32.2,35.7,32.9
XS GIS Cut Line= 6
2271858.45204316717239.6217569732271448.60904113717252.958369325
2271405.57162344717264.8594972172271334.94585398717337.381260486
2271263.84608607717383.3591104022271071.12663018717615.214161758
#Sta/Elev= 30
       0 1960.15    14.3 1956.06    26.3 1956.97    46.3 1948.46    66.3 1943.74
    74.3 1940.23    86.3  1938.2   118.3 1937.35   150.4  1930.6   170.4 1930.75
   182.4  1932.5   214.4 1925.12   270.4 1920.68   350.5 1917.34   366.5 1917.97
   382.5 1914.76   490.4 1909.69   504.6 1908.54   518.8 1909.73   588.1  1911.1
   649.3 1915.08   666.3 1914.56   708.1 1918.73   732.5 1919.03   748.1 1924.84
   770.6 1928.63   791.4 1937.12   805.4 1939.55     847 1952.14   943.2 1987.06
#Mann= 5 ,-1,0
       0      .1       0     360     .06       0   490.4    .045       0
   518.8     .06       0  731.74      .1       0
Bank Sta=490.4,518.8
XS Rating Curve= 0 ,0
Exp/Cntr=0.3,0.1

Type RM Length L Ch R = 1 ,11847   ,186.6,187.2,191.8
XS GIS Cut Line= 6
 2271831.4985065717221.4847977292271421.65550447717234.821410081
2271378.61808678717246.7225379732271307.99231732717319.244301242
2271236.89254941717365.2221511582271044.17309353717597.077202514
#Sta/Elev= 30
       0 1955.33    19.3 1946.83    31.3 1944.83    47.3 1939.76    67.4 1937.85
    83.4 1938.17   131.4 1930.34   147.4 1929.99   159.4 1932.09   167.4 1931.81
   183.4 1926.18   191.4 1924.64   287.5 1918.33   338.8 1916.29   355.5 1917.41
   367.5 1913.53  486.841909.155   509.7 1907.87   521.2 1909.12   531.1    1910
   539.7 1908.91   560.9 1911.16   589.4 1911.02   628.1 1914.98   684.8 1915.34
   727.4 1920.05   772.9 1930.73   787.3 1937.08   815.5 1943.54   943.2 1987.72
#Mann= 7 ,-1,0
       0      .1       0  430.06     .06       0  486.84    .045       0
   521.2     .06       0  556.65      .1       0  593.41     .06       0
  731.74      .1       0
Bank Sta=486.84,521.2
XS Rating Curve= 0 ,0
Exp/Cntr=0.3,0.1

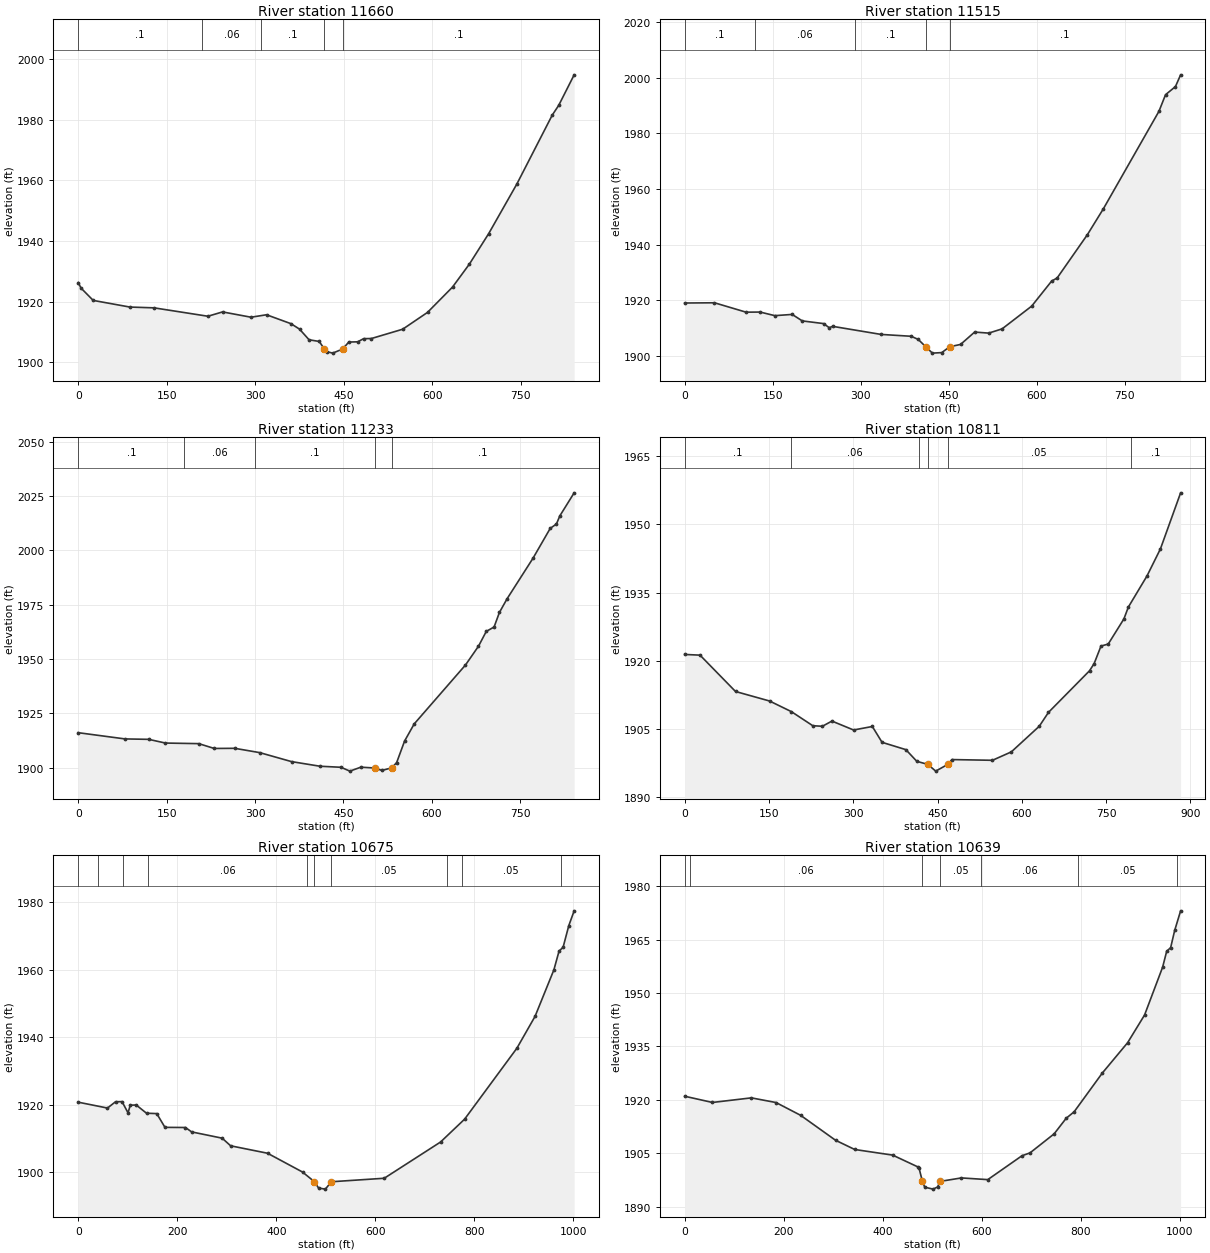
Type RM Length L Ch R = 1 ,11660   ,163.6,145.1,132.1
XS GIS Cut Line= 4
2271600.77514571717072.2295232862271242.62992031717166.340677407
2271132.83357383717249.1236370512270937.64006899717518.386105787
#Sta/Elev= 30
       0 1926.32     4.8 1924.49    25.4 1920.43    87.5 1918.24   128.5 1917.98
   219.8 1915.21   244.6 1916.64   292.8 1914.89   319.1  1915.7   360.4 1912.77
     375 1910.97   391.2 1907.45   408.4  1906.9  417.17  1904.4   421.5 1903.53
   431.2 1903.05   448.1  1904.4   458.5  1906.7   473.6 1906.78   483.6 1907.81
   496.9 1907.87   549.8 1910.93   591.9 1916.48   634.3 1924.83     663 1932.44
   695.6 1942.46   743.2 1958.77   803.3 1981.54   814.2 1984.73   840.4 1994.81
#Mann= 5 ,-1,0
       0      .1       0     210     .06       0     310      .1       0
  417.17    .045       0   448.1      .1       0
Bank Sta=417.17,448.1
XS Rating Curve= 0 ,0
Exp/Cntr(USF)=0,0
Exp/Cntr=0.3,0.1

Type RM Length L Ch R = 1 ,11515   ,264.3,282,285.4
XS GIS Cut Line= 4
2271273.92356344716775.6729304582271070.19031205717064.714824365
2271067.33212406717233.2327553972270898.75371431 717508.71899997
#Sta/Elev= 30
       0 1919.04    50.8 1919.12   104.6 1915.75   128.6 1915.79   153.6  1914.5
   183.2 1914.94   200.4 1912.61   236.7 1911.65   246.3 1910.17   252.1 1910.66
   334.6 1907.76   386.1 1907.09   398.1 1905.94  410.751903.339   422.1 1901.04
   438.1 1901.23  451.66 1903.34   470.1 1904.16   494.1  1908.6   518.1 1908.23
   540.9 1909.75   591.3 1917.92   625.3 1926.91   634.7 1928.03   686.2 1943.57
   713.5 1952.89   808.2  1987.9   819.4 1993.85   836.3 1996.77   845.1 2000.99
#Mann= 5 ,-1,0
       0      .1       0     120     .06       0     290      .1       0
  410.75    .045       0  451.66      .1       0
Bank Sta=410.75,451.66
XS Rating Curve= 0 ,0
Exp/Cntr=0.3,0.1

Type RM Length L Ch R = 1 ,11233   ,419.8,422,420.8
XS GIS Cut Line= 4
2271128.04215779716705.7801320742270936.36474345716959.990603584
 2270784.1103434717139.4332893552270663.12247193717400.440832294
#Sta/Elev= 30
       0 1916.09    79.4 1913.22   119.5 1913.03     148 1911.32   204.6 1911.05
   230.8 1908.83   265.5  1908.9   307.9 1906.92   361.9 1902.78   410.2 1900.65
   445.8 1900.17   460.9  1898.4   479.4 1900.21   503.8 1899.83   515.2  1898.7
   532.2 1899.94   540.3 1902.36   553.7 1912.24     570 1920.12     657 1947.23
   679.1 1955.89   692.3  1962.7   705.6 1964.74   714.6 1971.43   727.6 1977.72
   771.7 1996.43   800.8 2010.12   811.3 2012.12   817.1 2015.87   841.4 2026.48
#Mann= 5 ,-1,0
       0      .1       0     180     .06       0     300      .1       0
   503.8    .045       0   532.2      .1       0
Bank Sta=503.8,532.2
XS Rating Curve= 0 ,0
Exp/Cntr(USF)=0,0
Exp/Cntr=0.3,0.1

Type RM Length L Ch R = 1 ,10811   ,141.3,136,133.6
XS GIS Cut Line= 4
2270985.70169692716550.2259954532270688.78623294716661.278350709
2270484.40407285716862.0522896492270433.17775507717136.551519208
#Sta/Elev= 30
       0 1921.43    27.3 1921.28    90.5 1913.29   151.1  1911.2     190 1908.86
     228 1905.77   245.1 1905.65   262.1 1906.79   300.6 1904.83     334  1905.6
   351.3 1902.12   393.7 1900.51   413.2 1897.94   432.81897.271   446.8 1895.79
  467.98 1897.25   475.8 1898.33   547.8 1898.17   581.4 1900.02   631.1 1905.65
   647.5  1908.7   720.6 1917.85   728.8 1919.43     741 1923.28   753.8 1923.71
   781.7 1929.23   789.8 1931.87   822.8 1938.67   846.8 1944.64   882.7 1956.95
#Mann= 6 ,-1,0
       0      .1       0     190     .06       0     417      .1       0
   432.8    .045       0  467.98     .05       0   793.5      .1       0
Bank Sta=432.8,467.98
XS Rating Curve= 0 ,0
Exp/Cntr=0.3,0.1

Type RM Length L Ch R = 1 ,10675   ,36.3,36.3,36.5
XS GIS Cut Line= 6
2270949.26942885716525.7559907672270511.95854218716643.983546105
2270495.26326334716655.4173770952270470.14134535716695.233247125
2270444.07143045716785.292953146 2270378.9701716717167.175047994
#Sta/Elev= 30
       0  1920.8    59.1 1919.06    75.4 1920.93    88.5 1920.96   100.6 1917.64
   105.1 1919.91   117.2 1919.96   137.9 1917.53   158.6 1917.42   175.2 1913.34
   216.6  1913.3     229    1912   290.7 1910.14   307.8 1907.88   382.3 1905.68
     453 1900.11  477.121897.231   485.4 1895.37   499.1 1895.05  511.191897.232
     618 1898.27   731.7    1909   780.4 1915.79   885.9 1936.79   922.5  1946.2
   960.6    1960     971 1965.54   979.2 1966.69   990.7  1973.1  1001.5 1977.47
#Mann= 10 ,-1,0
       0      .1       0      40     .06       0      90      .1       0
     140     .06       0  463.01     .05       0  477.12    .045       0
  511.19     .05       0  744.11     .06       0  774.11     .05       0
  974.11      .1       0
Bank Sta=477.12,511.19
XS Rating Curve= 0 ,0
Exp/Cntr(USF)=0,0
Exp/Cntr=0.3,0.1

Type RM Length L Ch R = 1 ,10639   ,177.7,166.8,159.8
XS GIS Cut Line= 6
2270918.20148941716507.5630532542270480.89060273716625.790608591
 2270464.1953239716637.224439581 2270439.0734059716677.040309612
  2270413.003491716767.1000156332270347.90223216 717148.98211048
#Sta/Elev= 30
       0 1921.02      56 1919.27   134.7 1920.56   184.4 1919.25   234.1 1915.66
   304.6 1908.65   343.4 1906.05     420 1904.47   470.4 1901.19   473.2 1900.85
  480.141897.076   484.8 1895.45   501.7 1894.91   510.9 1895.54  515.461897.073
   558.8 1898.06   612.1 1897.58   681.1 1904.29   697.4  1905.1   746.1 1910.45
   770.4 1914.82   786.5 1916.65   843.4 1927.54   894.5 1936.07   928.7 1943.85
   965.2 1957.31   973.3 1961.73   981.4 1962.81   989.5 1967.61  1001.5 1973.13
#Mann= 7 ,-1,0
       0      .1       0      10     .06       0  480.14    .045       0
  515.46     .05       0  599.18     .06       0  794.11     .05       0
  994.11      .1       0
Bank Sta=480.14,515.46
XS Rating Curve= 0 ,0
Exp/Cntr(USF)=0,0
Exp/Cntr=0.3,0.1

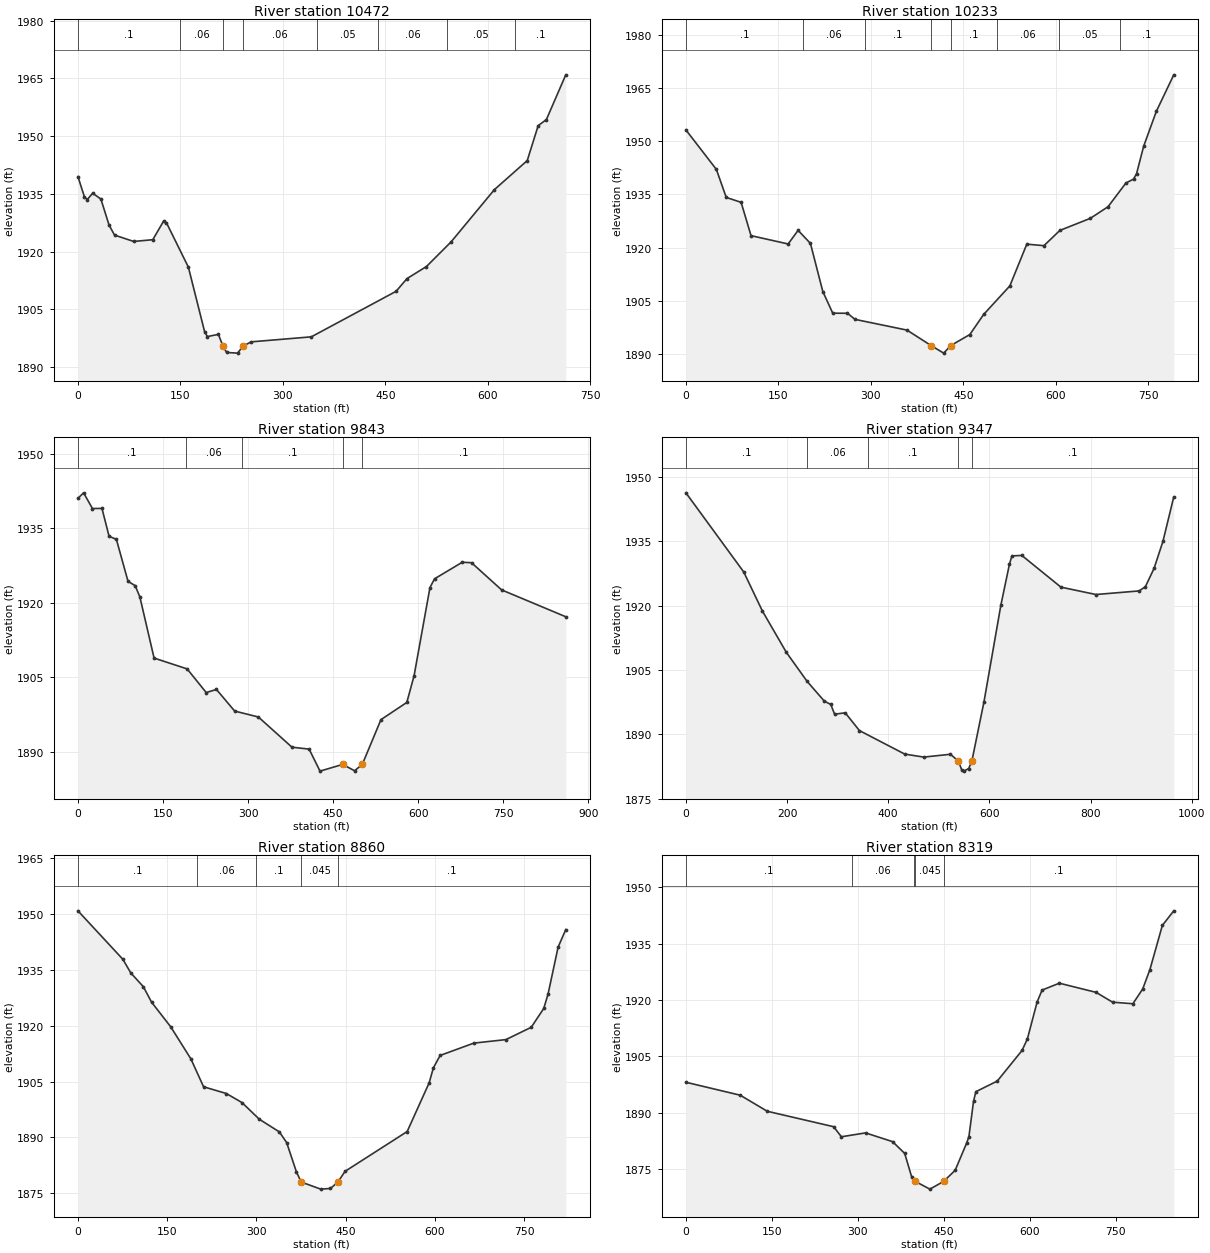
Type RM Length L Ch R = 1 ,10472   ,246.5,238.8,229.7
XS GIS Cut Line= 2
 2270291.3817154 716403.593615182270270.72927054717117.613705521
#Sta/Elev= 30
       0 1939.51     9.6  1934.2    13.6 1933.55    21.6 1935.19    33.6 1933.69
    45.6 1926.91    53.6 1924.32    81.6 1922.67   109.6 1923.12   125.6    1928
   129.6 1927.53   161.7    1916   185.7 1899.07   189.7 1897.97   205.7 1898.53
   212.3 1895.48   217.7 1893.83   233.7 1893.66   241.9 1895.49   253.7 1896.59
   341.7 1897.89   465.8 1909.71   481.8 1913.02   510.3 1916.16   546.4 1922.56
   609.8 1936.13   657.9 1943.68   673.9 1952.75   685.9 1954.32   714.3 1965.95
#Mann= 8 ,-1,0
       0      .1       0     150     .06       0   212.3    .045       0
   241.9     .06       0     350     .05       0     440     .06       0
     540     .05       0     640      .1       0
Bank Sta=212.3,241.9
XS Rating Curve= 0 ,0
Exp/Cntr(USF)=0,0
Exp/Cntr=0.3,0.1

Type RM Length L Ch R = 1 ,10233   ,364.2,390.6,402.6
XS GIS Cut Line= 4
2270110.72875769716360.0022057922270078.95452589716727.701767451
2270134.72557925716817.0714944872270210.64103419717124.560808779
#Sta/Elev= 30
       0 1953.16    49.4 1942.05    65.4 1934.16    89.5 1932.79   105.6 1923.41
   165.8 1921.07   181.9  1924.9   201.9 1921.24     222 1907.69   238.1 1901.59
     262 1901.57   274.2 1899.85   358.5 1896.83  397.671892.471     418 1890.35
  429.43 1892.47   460.4 1895.58   482.8 1901.23   525.3 1909.27   552.8 1921.02
   580.6 1920.59   606.4 1924.88   655.8 1928.28   684.6 1931.56   713.5 1938.22
   725.9 1939.33   730.8 1940.87   742.3 1948.57   762.9 1958.41   791.1 1968.67
#Mann= 8 ,-1,0
       0      .1       0     190     .06       0     290      .1       0
  397.67    .045       0  429.43      .1       0  504.41     .06       0
  604.41     .05       0  704.41      .1       0
Bank Sta=397.67,429.43
XS Rating Curve= 0 ,0
Exp/Cntr=0.3,0.1

Type RM Length L Ch R = 1 ,9843    ,495.6,495.2,493.3
XS GIS Cut Line= 4
  2269912.126127716372.6355397122269816.28822969716689.612968189
2269700.52455856716877.658022871 2269641.2188286717180.248814274
#Sta/Elev= 30
       0 1940.98      10 1942.09    25.6 1938.93    42.4 1938.95    54.9 1933.34
    67.8 1932.73    88.3 1924.28   100.9  1923.4   109.2 1921.14   134.3 1908.82
   192.6 1906.64   226.2 1901.88   244.3  1902.5   276.4 1898.15   318.2 1896.96
   377.4 1890.88   407.7 1890.49   426.9 1886.06   466.9 1887.41   487.9 1886.13
  501.481887.421   534.4 1896.43     580 1899.89   592.8 1905.27   620.8 1923.02
   628.9 1924.78   677.7 1928.11   694.1 1928.02   747.1 1922.55   860.3 1917.14
#Mann= 5 ,-1,0
       0      .1       0     190     .06       0     290      .1       0
   466.9    .045       0  501.48      .1       0
Bank Sta=466.9,501.48
XS Rating Curve= 0 ,0
Exp/Cntr=0.3,0.1

Type RM Length L Ch R = 1 ,9347    ,464.1,487.5,491.3
XS GIS Cut Line= 4
2269736.53797781716258.9885340432269430.60236398716457.173054946
2269326.85490942716681.774601485     2269262.022 717028.44328845
#Sta/Elev= 30
       0  1946.3   114.4 1927.84   151.2 1918.76   198.5 1909.14   239.5 1902.38
   273.7 1897.75   286.4 1896.98     294 1894.71     315 1895.03   343.1 1890.89
   432.7 1885.41   470.3 1884.71   523.1 1885.37  538.781883.774   545.2 1881.77
   549.6 1881.44   559.2 1882.05  565.421883.776   589.4 1897.62   622.8 1920.15
   639.8 1929.71   644.6  1931.6   664.2 1931.71   741.5 1924.32   810.7  1922.6
   896.2 1923.44   908.5 1924.42   925.7  1928.7   943.2 1934.98   964.6 1945.34
#Mann= 5 ,-1,0
       0      .1       0     240     .06       0     360      .1       0
  538.78    .045       0  565.42      .1       0
Bank Sta=538.78,565.42
XS Rating Curve= 0 ,0
Exp/Cntr=0.3,0.1

Type RM Length L Ch R = 1 ,8860    ,571,541.1,500.9
XS GIS Cut Line= 4
2269618.61142855716070.7437857082269308.43907882716183.790090307
2269116.94546428716225.147351394 2268894.3928429716417.361800006
#Sta/Elev= 30
       0 1950.81    75.6 1937.79    88.9 1934.14   109.9 1930.46   123.9 1926.27
   155.9  1919.7   189.9 1911.07   211.2 1903.59   249.5 1901.78   275.8 1899.35
   304.9 1894.88   338.6 1891.48   350.9 1888.61   367.2 1880.79  375.26 1878.03
   408.2 1876.12   424.5 1876.29  437.04 1878.03   449.1  1880.9   553.5 1891.58
   590.5 1904.67   597.5 1908.66   608.9    1912   665.6 1915.31   719.5 1916.25
     762 1919.55   783.1 1924.61   790.4 1928.52   807.2 1941.06   820.1 1945.78
#Mann= 5 ,-1,0
       0      .1       0     200     .06       0     300      .1       0
  375.26    .045       0  437.04      .1       0
Bank Sta=375.26,437.04
XS Rating Curve= 0 ,0
Exp/Cntr=0.3,0.1

Type RM Length L Ch R = 1 ,8319    ,427.7,432.3,436.1
XS GIS Cut Line= 4
2269090.14481664715492.605148171 2268954.7595575715844.993557503
2268948.40320002715973.0273656262268825.01671786716295.755264547
#Sta/Elev= 30
       0 1898.07    94.8 1894.62     142 1890.34   257.7 1886.23   271.3 1883.55
   313.4 1884.58   360.6 1882.25   381.7 1879.12   393.7 1872.96  400.221871.654
   425.7  1869.6  449.661871.655   469.8 1874.62   489.8 1881.85   493.8  1883.6
   501.8 1892.95   505.9 1895.56   543.2 1898.38   586.5 1906.54   595.8 1909.61
   612.9 1919.51   621.5 1922.63   651.6 1924.46   715.7 1922.02   744.5  1919.4
   779.9 1918.99   797.1 1922.94   809.6 1928.09   831.3 1939.85   851.2 1943.74
#Mann= 5 ,-1,0
       0      .1       0     290     .06       0   397.5      .1       0
  400.22    .045       0  449.66      .1       0
Bank Sta=400.22,449.66
XS Rating Curve= 0 ,0
Exp/Cntr=0.3,0.1

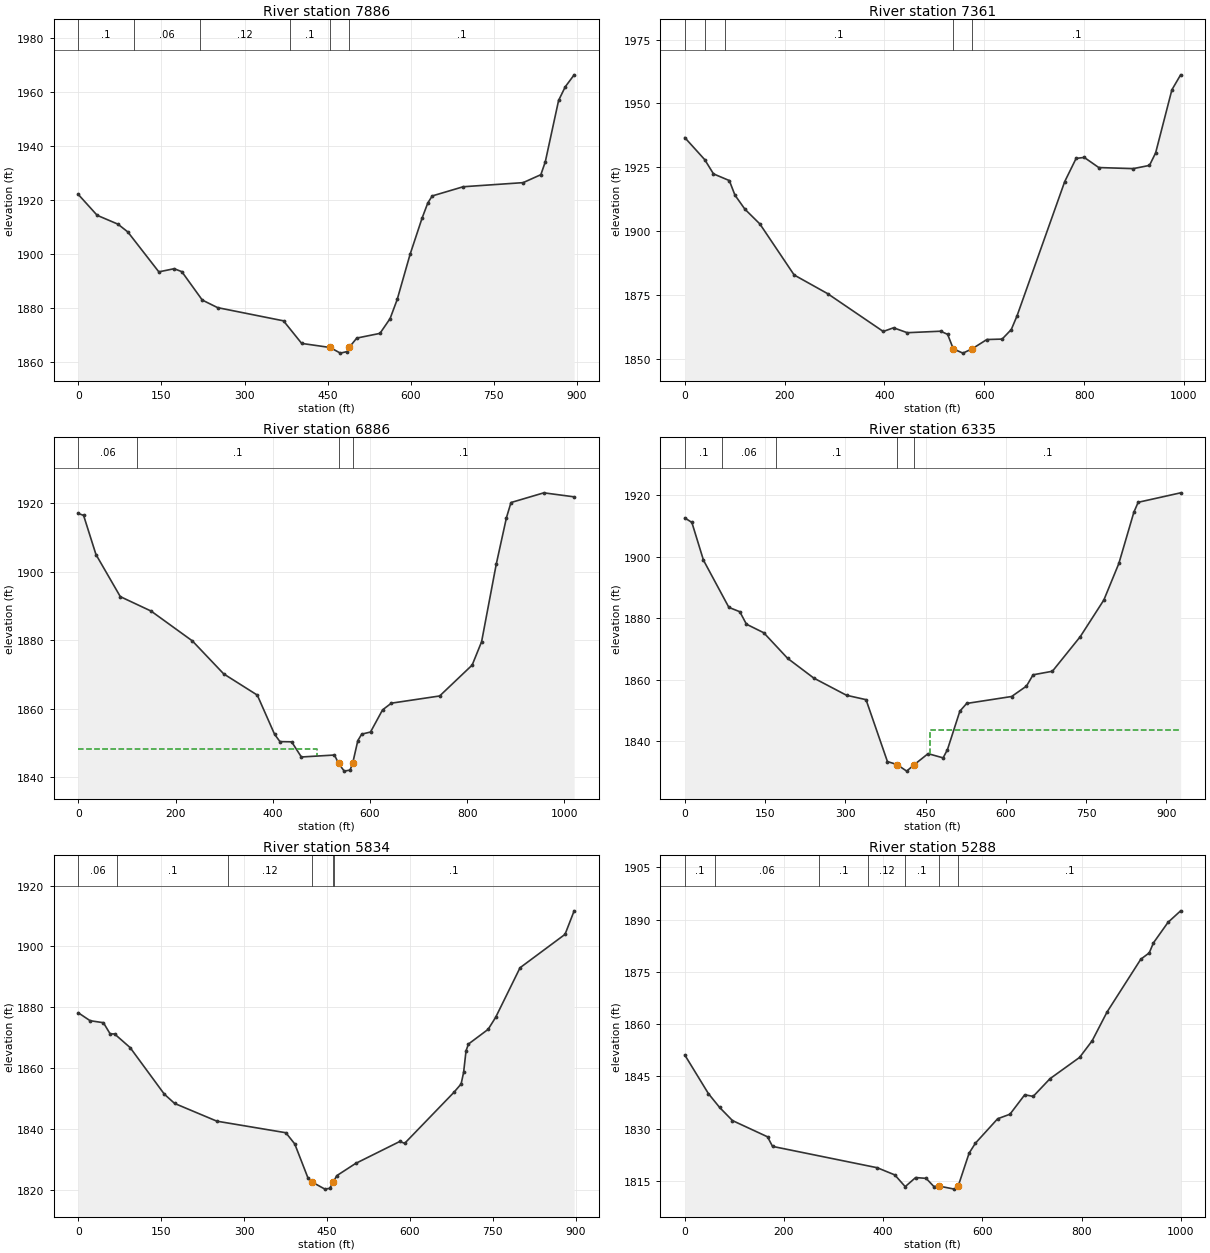
Type RM Length L Ch R = 1 ,7886    ,533,525.5,511.9
XS GIS Cut Line= 4
     2268736.621      715379.1482268556.36745038715693.059464378
2268515.90394056715870.9178776092268528.08757148716221.236757142
#Sta/Elev= 30
       0 1921.92      34  1914.2    71.5 1910.92    89.3 1908.04   145.3 1893.24
     173 1894.41   186.8 1893.31   223.7 1882.79   251.4 1879.98   370.3 1875.09
   403.1 1866.72  454.431865.209   472.9 1863.12   485.2  1863.7  488.661865.211
   502.6  1868.7   544.4 1870.44   562.7 1875.93   575.5    1883   598.7 1899.69
   620.3 1913.09   630.7 1918.75   638.7 1921.38   694.7 1924.79   802.8 1926.31
   834.8 1929.26   842.8 1934.03   866.8 1956.77   878.8 1961.83   894.9 1966.27
#Mann= 6 ,-1,0
       0      .1       0     100     .06       0     220     .12       0
  381.98      .1       0  454.43    .045       0  488.66      .1       0
Bank Sta=454.43,488.66
XS Rating Curve= 0 ,0
Exp/Cntr=0.3,0.1

Type RM Length L Ch R = 1 ,7361    ,439.1,474.7,503.9
XS GIS Cut Line= 4
2268399.83464377715340.6634868032268095.81623602715764.788708048
 2268149.0262545715886.196690689 2268217.1263549716218.342117131
#Sta/Elev= 30
       0 1936.64      40    1928    57.5 1922.45    89.2 1919.84   100.5 1914.13
   120.5 1908.63   150.5 1902.85   219.1 1882.91   286.1 1875.62   397.6 1860.82
   418.2 1862.26   445.7 1860.34   512.5 1860.92   526.6 1859.69  537.971854.017
   557.2 1852.35  575.511854.017   605.2 1857.67   635.8 1857.84   654.1 1861.57
   665.6  1866.9   761.2 1919.44     784  1928.5   800.3 1928.89   829.4 1924.93
   898.3  1924.5     931 1925.77   943.3 1930.65   975.9 1955.33   993.4 1961.19
#Mann= 5 ,-1,0
       0      .1       0      40     .06       0      80      .1       0
  537.97    .045       0  575.51      .1       0
Bank Sta=537.97,575.51
XS Rating Curve= 0 ,0
Exp/Cntr=0.3,0.1

Type RM Length L Ch R = 1 ,6886    ,567.8,551.4,522.3
XS GIS Cut Line= 4
  2268238.396127715280.2139365332267966.16487868715590.698943686
2267781.81150792715601.7846666772267623.58663497715993.855523815
#Sta/Elev= 30
       0 1916.91    10.8 1916.36    36.3 1904.95    86.4 1892.68   149.7 1888.48
   234.7 1879.78   299.2 1870.17   368.3 1863.99   403.8  1852.6   414.9 1850.44
     439 1850.38     459 1845.96   527.1 1846.53  535.641844.086   547.2 1841.84
   559.2 1842.15  564.521844.091   575.2 1850.74   583.2 1852.62   601.3 1853.23
   626.1 1859.69   644.2 1861.64   743.6 1863.74   810.5 1872.74   829.9 1879.54
   860.1 1902.16   881.1 1915.71   890.4  1920.1     958 1922.93  1020.4 1921.76
#Mann= 4 ,-1,0
       0     .06       0     120      .1       0  535.64    .045       0
  564.52      .1       0
#XS Ineff= 2 , 0
          490.51 1848.42
Permanent Ineff=
       F       F
Bank Sta=535.64,564.52
XS Rating Curve= 0 ,0
Exp/Cntr=0.3,0.1

Type RM Length L Ch R = 1 ,6335    ,505.8,500.8,493.3
XS GIS Cut Line= 4
2267557.36892406715008.1784683832267495.29406255715336.769356046
2267490.79234175715553.8736710222267515.38911408715928.405227836
#Sta/Elev= 30
       0 1912.54    13.2 1911.08    34.9  1898.8    82.4 1883.46   102.8 1882.05
   115.2    1878   147.6 1875.21   192.3 1866.88   241.2 1860.47   302.3 1854.89
   338.8 1853.46   378.8 1833.34  396.641832.378   414.8 1830.23  429.261832.376
   454.8 1835.91   482.9 1834.54     491 1837.22   514.2 1849.72   526.9 1852.23
     611 1854.49   638.7 1857.87   651.1 1861.54   687.2  1862.7   739.3 1873.95
   783.4 1885.87   811.4 1897.73   839.5  1914.4   847.5 1917.62   926.9  1920.7
#Mann= 5 ,-1,0
       0      .1       0      70     .06       0     170      .1       0
  396.64    .045       0  429.26      .1       0
#XS Ineff= 2 , 0
                          458.49         1843.63
Permanent Ineff=
       F       F
Bank Sta=396.64,429.26
XS Rating Curve= 0 ,0
Exp/Cntr=0.3,0.1

Type RM Length L Ch R = 1 ,5834    ,549.5,545.9,535.9
XS GIS Cut Line= 4
2266968.93455704715108.0039620272267012.40112428715508.632651419
2267045.27496441715598.7257457372267218.01582144 715957.41132571
#Sta/Elev= 30
       0 1878.18    21.3 1875.59    45.4 1874.93    57.5 1871.27    65.6 1871.23
    93.7 1866.75   155.6 1851.43   174.2 1848.39   250.6 1842.56   375.4 1838.76
   391.5 1835.09   415.7 1823.77  423.271822.511   446.1 1820.22   454.7 1820.47
  461.261822.513   467.4 1824.63   501.6 1828.66   581.5 1835.88   590.4 1835.28
   679.2 1851.99   692.5 1854.79     697 1858.59   701.4 1865.69   705.8 1867.92
   741.3 1872.74   754.9 1876.67   799.1    1893   880.5 1903.98     897 1911.71
#Mann= 6 ,-1,0
       0     .06       0      70      .1       0     270     .12       0
  423.27    .045       0  461.26     .12       0  462.98      .1       0
Bank Sta=423.27,461.26
XS Rating Curve= 0 ,0
Exp/Cntr=0.3,0.1

Type RM Length L Ch R = 1 ,5288    ,440,442.3,441.5
XS GIS Cut Line= 4
 2266449.9872234715408.3786212762266564.38701593715805.362631991
 2266689.0684601715951.808925029     2267059.647      716086.304
#Sta/Elev= 30
       0 1851.13    47.7 1840.03    70.3 1836.07    96.1 1832.32   166.8 1827.66
   176.9 1824.91     388 1818.79   423.4 1816.73   444.4 1813.36   465.4 1815.97
   486.6 1815.74   502.2 1813.39   512.2 1813.54   543.4 1812.65  551.21 1813.52
   573.2 1822.96   585.9 1825.82   630.8 1832.84   655.6 1834.14   685.4 1839.72
   702.4 1839.25   736.4 1844.34     796 1850.44   821.3  1855.2   851.3 1863.45
   919.4 1878.61   936.4 1880.42   944.9  1883.3   974.3 1889.19   999.7 1892.49
#Mann= 7 ,-1,0
       0      .1       0      60     .06       0     270      .1       0
     370     .12       0  443.14      .1       0   512.2    .045       0
  551.21      .1       0
Bank Sta=512.2,551.21
XS Rating Curve= 0 ,0
Exp/Cntr=0.3,0.1