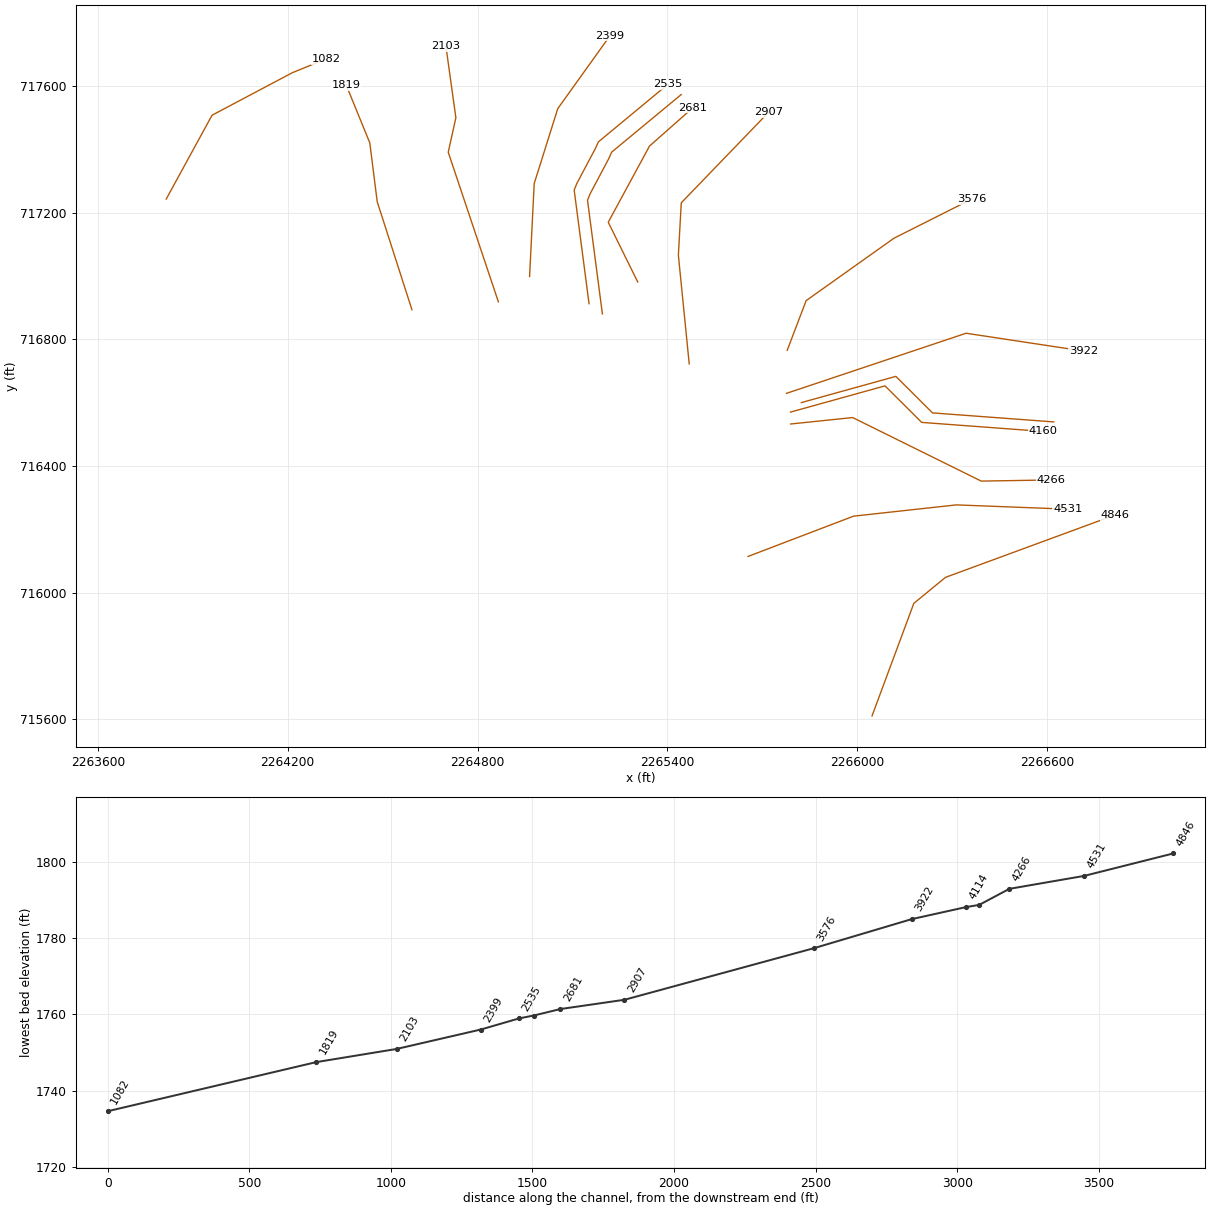
HEC-RAS study BEAVCK2.prj: BEAVCK2

--- BEAVCK2.g01 (geometry) --- (continued)

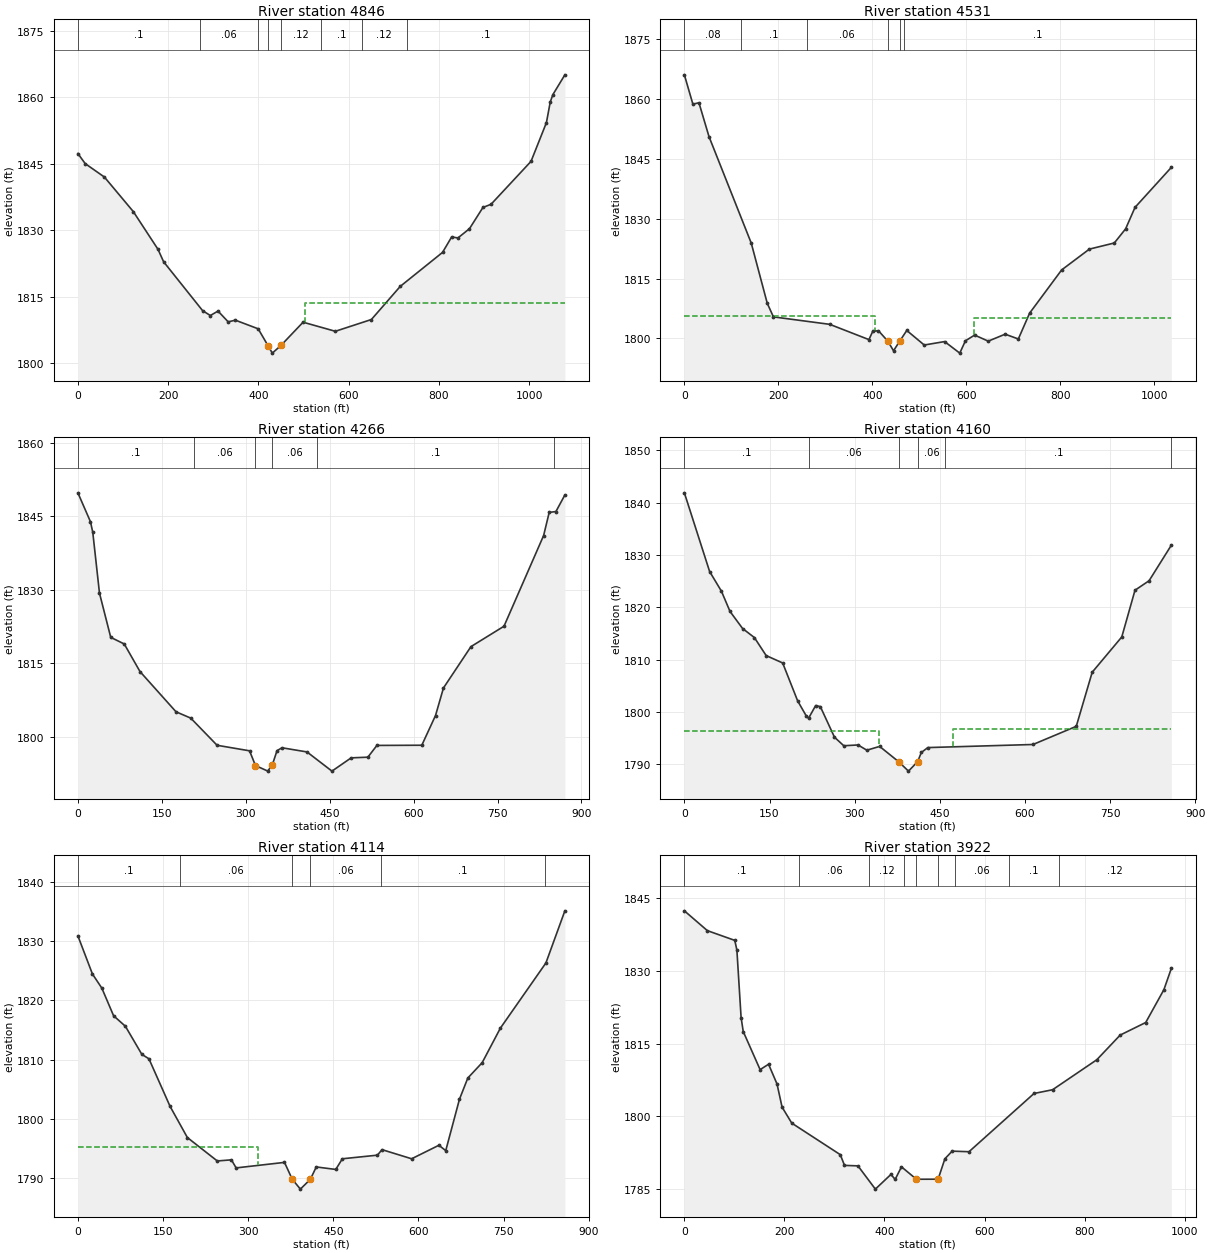
Type RM Length L Ch R = 1 ,4846    ,319.9,315.1,306.1
XS GIS Cut Line= 4
     2266047.098      715610.0322266179.14560041715965.692232847
2266279.30255112716047.8809548082266814.59205947716244.815680243
#Sta/Elev= 30
       0 1847.29    16.2 1845.02    58.8 1841.98   122.8 1834.19   177.5 1825.68
     190 1822.86   276.4 1811.83   293.5 1810.73   310.6 1811.73   333.1  1809.3
     349 1809.68   399.6 1807.73  421.111803.961   430.9 1802.24  449.941803.962
   499.1 1809.22   570.6 1807.17   650.5 1809.83   714.5 1817.31   808.2 1824.98
   828.4 1828.47   842.3 1828.24   867.9 1830.33   897.7 1835.12   915.7 1835.84
  1004.3 1845.53  1038.4 1854.27  1046.9 1858.93  1052.8 1860.61  1079.3 1865.06
#Mann= 8 ,-1,0
       0      .1       0     270     .06       0  399.38     .12       0
  421.11    .045       0  449.94     .12       0  538.94      .1       0
  628.94     .12       0  728.94      .1       0
#XS Ineff= 2 , 0
                           502.6         1813.61
Permanent Ineff=
       F       F
Bank Sta=421.11,449.94
XS Rating Curve= 0 ,0
Exp/Cntr=0.3,0.1

Type RM Length L Ch R = 1 ,4531    ,267.9,264.3,250.6
XS GIS Cut Line= 4
 2265655.2301399716114.0449323342265988.75797402716241.371702525
2266313.69443589716276.9799653772266665.46689748 716263.40507846
#Sta/Elev= 30
       0 1865.96    18.1 1858.63      31 1858.97    52.4  1850.5   142.3 1823.85
   176.3 1808.81   189.4 1805.41   309.3 1803.54   392.6 1799.72   400.7 1801.79
   412.8 1801.95   432.9 1799.32   444.9 1796.92457.89861799.312   473.1 1802.01
   510.2 1798.37   553.6 1799.23   585.8 1796.34   597.9 1799.43   617.4 1800.85
   646.4 1799.34   682.4 1801.08   710.4 1799.88   734.4 1806.34   802.5 1817.15
   861.5 1822.36   914.5 1823.89   938.6 1827.43   958.6  1832.8  1035.9 1842.81
#Mann= 6 ,-1,0
       0     .08       0     120      .1       0     260     .06       0
   432.9    .045       0457.8986     .06       0  467.01      .1       0
#XS Ineff= 2 , 0
          404.46 1805.55   617.1         1805.15
Permanent Ineff=
       F       F
Bank Sta=432.9,457.8986
XS Rating Curve= 0 ,0
Exp/Cntr(USF)=0,0
Exp/Cntr=0.3,0.1

Type RM Length L Ch R = 1 ,4266    ,114.6,106.7,103.5
XS GIS Cut Line= 4
2265789.74824464716532.6898485422265985.78326567716553.010551942
2266392.19733366716352.1941889342266612.13906457716355.780195416
#Sta/Elev= 30
       0 1849.79    22.5 1843.88    26.6 1841.73    38.6 1829.29    58.7 1820.27
    82.9 1818.91     111 1813.28   175.4 1805.06   201.7 1803.77   248.8 1798.22
   306.8 1797.09   317.4 1794.08   339.1 1792.96  347.17  1794.1   355.9 1797.12
   364.8 1797.71   409.5 1796.86   454.1 1792.94   488.4 1795.65   518.3 1795.79
   534.4 1798.19   614.7 1798.23   639.2  1804.3   653.4 1809.93   702.5 1818.37
   761.6 1822.54   832.4 1841.06   842.4 1845.79   854.4 1845.97   870.4 1849.35
#Mann= 6 ,-1,0
       0      .1       0  207.09     .06       0   317.4    .045       0
  347.17     .06       0  427.09      .1       0  850.41     .12       0
Bank Sta=317.4,347.17
XS Rating Curve= 0 ,0
Exp/Cntr(USF)=0,0
Exp/Cntr=0.3,0.1

Type RM Length L Ch R = 1 ,4160    ,45.6,45.6,45.6
XS GIS Cut Line= 4
2265789.30040363716570.2751407642266088.09082753716653.222930087
2266204.00137487716537.7330683382266587.27473932716509.231783054
#Sta/Elev= 30
       0  1841.9    44.5 1826.86    65.3  1823.1    80.4 1819.24   102.6 1815.97
   123.4 1814.24   144.1  1810.8   173.2 1809.39   199.6 1802.14   214.7 1799.28
   218.8 1798.82   231.3 1801.25   239.6 1801.04   264.5  1795.2   280.9 1793.57
     306 1793.72   321.5 1792.72   344.1 1793.44   377.41790.534   394.9 1788.72
  411.021790.535   417.5 1792.28     429 1793.22   614.3 1793.81   690.5 1797.28
   718.6 1807.62   770.7 1814.36     794 1823.29   818.8  1825.1     858 1831.89
#Mann= 6 ,-1,0
       0      .1       0     220     .06       0   377.4    .045       0
  411.02     .06       0  460.09      .1       0  858.05     .12       0
#XS Ineff= 2 , 0
          342.82 1796.37  472.57         1796.69
Permanent Ineff=
       F       F
Bank Sta=377.4,411.02
XS Rating Curve= 0 ,0
Exp/Cntr(USF)=0,0
Exp/Cntr=0.3,0.1

Type RM Length L Ch R = 1 ,4114    ,167,192.5,208.4
XS GIS Cut Line= 4
2265823.55314823716600.2994541472266122.34357213716683.247243469
2266238.25411947716567.7573817212266621.52748391716539.256096437
#Sta/Elev= 30
       0 1830.88    25.6 1824.45    42.2 1822.06    62.9  1817.4    83.7 1815.63
   112.7 1810.89   125.2 1810.14   162.5  1802.1   192.9 1796.86   245.6 1792.91
   270.5  1793.1   278.8 1791.74     364 1792.67  377.681789.824     392 1788.16
  409.591789.822     420  1791.9   454.3 1791.48     466 1793.28   527.8 1793.89
   535.8 1794.82     588 1793.28   636.1 1795.56   648.1 1794.65   672.3 1803.33
     687  1806.9   712.3 1809.49   744.4 1815.32   824.6 1826.31     858  1835.1
#Mann= 6 ,-1,0
       0      .1       0     180     .06       0  377.68    .045       0
  409.59     .06       0  533.72      .1       0  823.72     .12       0
#XS Ineff= 2 , 0
          318.04 1795.33
Permanent Ineff=
       F       F
Bank Sta=377.68,409.59
XS Rating Curve= 0 ,0
Exp/Cntr(USF)=0,0
Exp/Cntr=0.3,0.1

Type RM Length L Ch R = 1 ,3922    ,338.1,345.8,350.5
XS GIS Cut Line= 3
 2265776.5995542716629.512023564 2266344.3839139716819.570367126
2266714.93791707716763.389598903
#Sta/Elev= 30
       0 1842.42      46 1838.33   100.8 1836.32     105  1834.3   113.4 1820.38
   117.7 1817.51   151.4 1809.65   168.3 1810.76   185.2 1806.69   195.3 1801.91
   214.7 1798.61   311.7  1792.1   320.1 1789.89     347 1789.79   381.8 1784.99
   412.9 1788.02   421.4    1787     434 1789.59  463.86 1787.03   507.21787.041
   520.8 1791.25   535.3 1792.83     569 1792.71     699 1804.73   736.1  1805.5
   824.5 1811.69   871.2 1816.78   922.2 1819.37   958.6 1826.15   973.5 1830.55
#Mann= 9 ,-1,0
       0      .1       0     230     .06       0     370     .12       0
     440      .1       0  463.86    .045       0   507.2      .1       0
     540     .06       0  648.75      .1       0  748.75     .12       0
Bank Sta=463.86,507.2
XS Rating Curve= 0 ,0
Exp/Cntr(USF)=0,0
Exp/Cntr=0.3,0.1

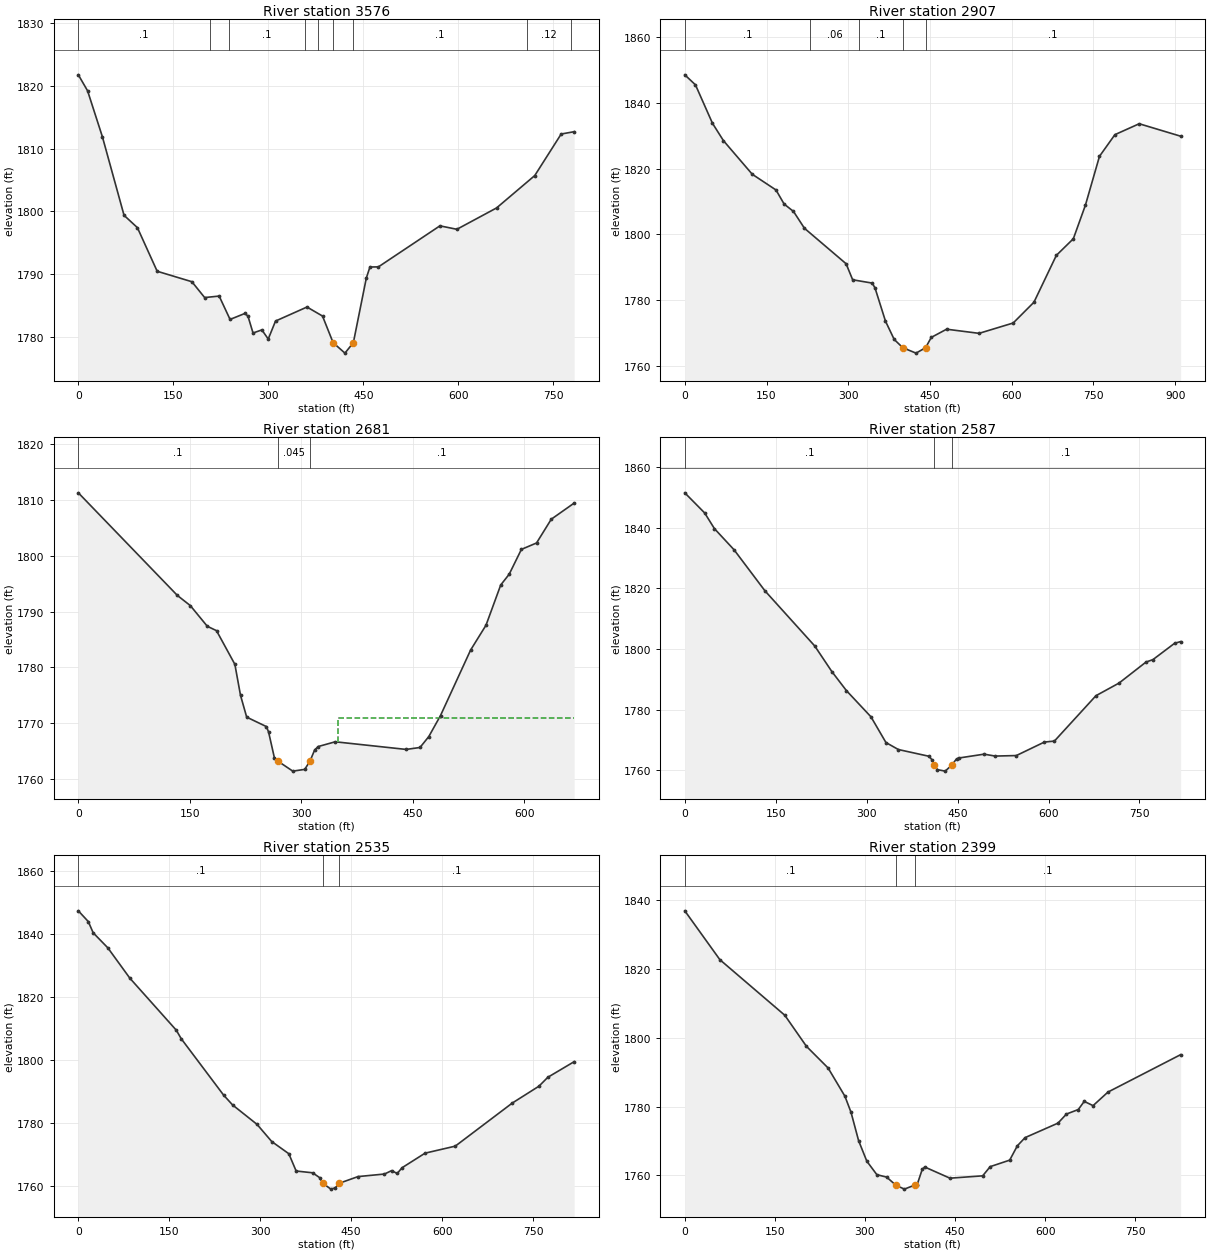
Type RM Length L Ch R = 1 ,3576    ,642.5,668.5,671
XS GIS Cut Line= 4
2265778.97739456716765.689577367 2265838.7269883 716922.60577387
2266116.36989996717119.8791826252266361.57167741717243.297544281
#Sta/Elev= 30
       0 1821.78    14.6 1819.23      38 1811.89    72.2 1799.35    93.3 1797.38
   124.5 1790.42   179.3 1788.75   199.5 1786.22   222.4 1786.46   239.6 1782.73
   262.9 1783.68   267.8 1783.28   275.9 1780.56   289.8 1781.06   299.9  1779.6
   311.4 1782.47   361.1 1784.71   385.6 1783.27  402.331779.024     421 1777.35
  434.331779.024   454.8 1789.34   460.5  1791.1   473.9 1791.12     571 1797.67
   597.8 1797.12   660.5 1800.53   720.8  1805.7   762.5 1812.33     783  1812.7
#Mann= 9 ,-1,0
       0      .1       0  207.91     .06       0  237.91      .1       0
  357.91     .12       0  377.91      .1       0  402.33    .045       0
  434.33      .1       0   708.5     .12       0   778.5      .1       0
Bank Sta=402.33,434.33
XS Rating Curve= 0 ,0
Exp/Cntr(USF)=0,0
Exp/Cntr=0.3,0.1

Type RM Length L Ch R = 1 ,2907    ,233.9,226.1,215.9
XS GIS Cut Line= 4
2265469.16972658716722.6421420082265434.87718954717066.281326296
 2265444.0613454717231.8618033612265721.00432527717518.910478734
#Sta/Elev= 30
       0 1848.52    19.6 1845.46    50.8 1833.77    70.9 1828.49   123.8 1818.26
   167.4 1813.47   182.3 1809.19   199.5 1806.94   219.6 1801.82     296 1791.03
   308.1 1786.14   344.2 1785.13   349.3 1783.56   368.3 1773.56   384.3 1767.99
  400.171765.458   424.4 1763.82  441.861765.458   452.4 1768.61   480.5  1771.1
   540.1 1769.84   602.7 1772.99   640.8 1779.31   681.9 1793.57   713.1 1798.63
   735.3 1808.87   761.1 1823.73   789.4 1830.31     834 1833.63     910 1829.84
#Mann= 5 ,-1,0
       0      .1       0     230     .06       0     320      .1       0
  400.17    .045       0  441.86      .1       0
Bank Sta=400.17,441.86
XS Rating Curve= 0 ,0
Exp/Cntr(USF)=0,0
Exp/Cntr=0.3,0.1

Type RM Length L Ch R = 1 ,2681    ,96.1,94.2,94.6
XS GIS Cut Line= 4
2265306.36113459716981.5834804552265213.25764284717170.450563724
2265343.60253129717411.1895923982265480.59766916717532.224131676
#Sta/Elev= 30
       0 1811.28   133.3 1792.88   150.7 1791.06   173.5 1787.36   185.9 1786.57
   210.6 1780.54   218.2 1774.98   226.5 1771.07   253.1 1769.37     256 1768.39
   263.7 1763.83   268.3  1763.2   288.5 1761.39   304.6  1761.7  311.75 1763.21
     318  1765.2   322.8  1765.8   345.6 1766.65   441.1 1765.28   459.7 1765.63
   471.5 1767.58   487.3 1771.36   527.8  1783.1   548.5 1787.55   568.3 1794.76
   579.7 1796.69   596.1 1801.14   616.5 1802.29   636.3 1806.55   667.1 1809.44
#Mann= 3 ,-1,0
       0      .1       0   268.3    .045       0  311.75      .1       0
#XS Ineff= 2 , 0
                          349.21          1770.9
Permanent Ineff=
       F       F
Bank Sta=268.3,311.75
XS Rating Curve= 0 ,0
Exp/Cntr(USF)=0,0
Exp/Cntr=0.3,0.1

Type RM Length L Ch R = 1 ,2587    ,52.3,52.3,52.2
XS GIS Cut Line= 6
2265194.70568707716880.6858915182265147.71358829717239.839789342
2265155.83236495717260.1836606452265214.44172096717370.750789438
2265224.19477554717392.2075095212265443.80779944 717573.99181147
#Sta/Elev= 30
       0 1851.57    32.8 1844.92    48.9 1839.74    81.2 1832.78   132.2 1819.22
   214.3 1801.02   242.5 1792.58   266.7 1786.25   307.1 1777.62   331.8 1769.13
   352.3 1766.82   402.9 1764.59   407.8 1763.42  411.451761.615   416.8 1760.17
   429.6 1759.69  439.991761.612   448.2 1763.72   452.7 1764.04   493.7 1765.29
     512 1764.66   546.9 1764.83   593.2 1769.29   609.7 1769.61   678.2 1784.59
   716.3 1788.76   760.8  1795.7   772.2  1796.5     808  1801.9   817.9 1802.45
#Mann= 3 ,-1,0
       0      .1       0  411.45    .045       0  439.99      .1       0
Bank Sta=411.45,439.99
XS Rating Curve= 0 ,0
Exp/Cntr(USF)=0,0
Exp/Cntr=0.3,0.1

Type RM Length L Ch R = 1 ,2535    ,132.6,135.3,137.1
XS GIS Cut Line= 6
2265152.51982477716912.9177863052265105.52772599717272.071684129
2265113.64650266717292.4155554322265172.25585867717402.982684224
2265182.00891325717424.4394043082265401.62193714717606.223706257
#Sta/Elev= 30
       0 1847.42    16.4 1844.01    24.5 1840.43    48.7 1835.64      85    1826
   161.6 1809.46   169.7 1806.76   239.6 1788.83   254.4  1785.7   294.8 1779.51
     319 1774.06   347.2 1770.18   359.3 1764.68   386.6 1764.11   398.4 1762.52
  403.521760.752   416.6 1758.92   424.2 1759.35  429.931760.751   461.4 1762.91
     505 1763.72   516.9 1764.81     526 1763.89     534 1765.72     572 1770.36
   621.8 1772.59   715.9  1786.3   759.8 1791.65   774.5 1794.49   817.9 1799.45
#Mann= 3 ,-1,0
       0      .1       0  403.52    .045       0  429.93      .1       0
Bank Sta=403.52,429.93
XS Rating Curve= 0 ,0
Exp/Cntr(USF)=0,0
Exp/Cntr=0.3,0.1

Type RM Length L Ch R = 1 ,2399    ,296.7,296.7,297.4
XS GIS Cut Line= 4
2264964.53831487716998.8741289232264979.16886358717292.815152884
2265053.65165698717529.5640319112265218.57784237717759.662661527
#Sta/Elev= 30
       0 1836.84    58.4 1822.65   166.5 1806.51   202.6 1797.47   238.6 1791.19
   266.6 1782.99   276.8 1778.31   289.4 1770.08   303.1 1764.11   319.8  1760.2
   336.1 1759.49  351.43 1757.15   365.6    1756   382.7 1757.16   386.9 1757.31
   395.3 1761.72   399.5 1762.43   441.5 1759.18     496 1759.86   508.5 1762.53
     541 1764.42   553.7 1768.58   566.6 1770.96   621.4 1775.17   635.5 1777.81
   655.2 1779.12   665.1 1781.49   679.8 1780.25   704.6 1784.19   825.6 1795.06
#Mann= 3 ,-1,0
       0      .1       0  351.43    .045       0   382.7      .1       0
Bank Sta=351.43,382.7
XS Rating Curve= 0 ,0
Exp/Cntr(USF)=0,0
Exp/Cntr=0.3,0.1

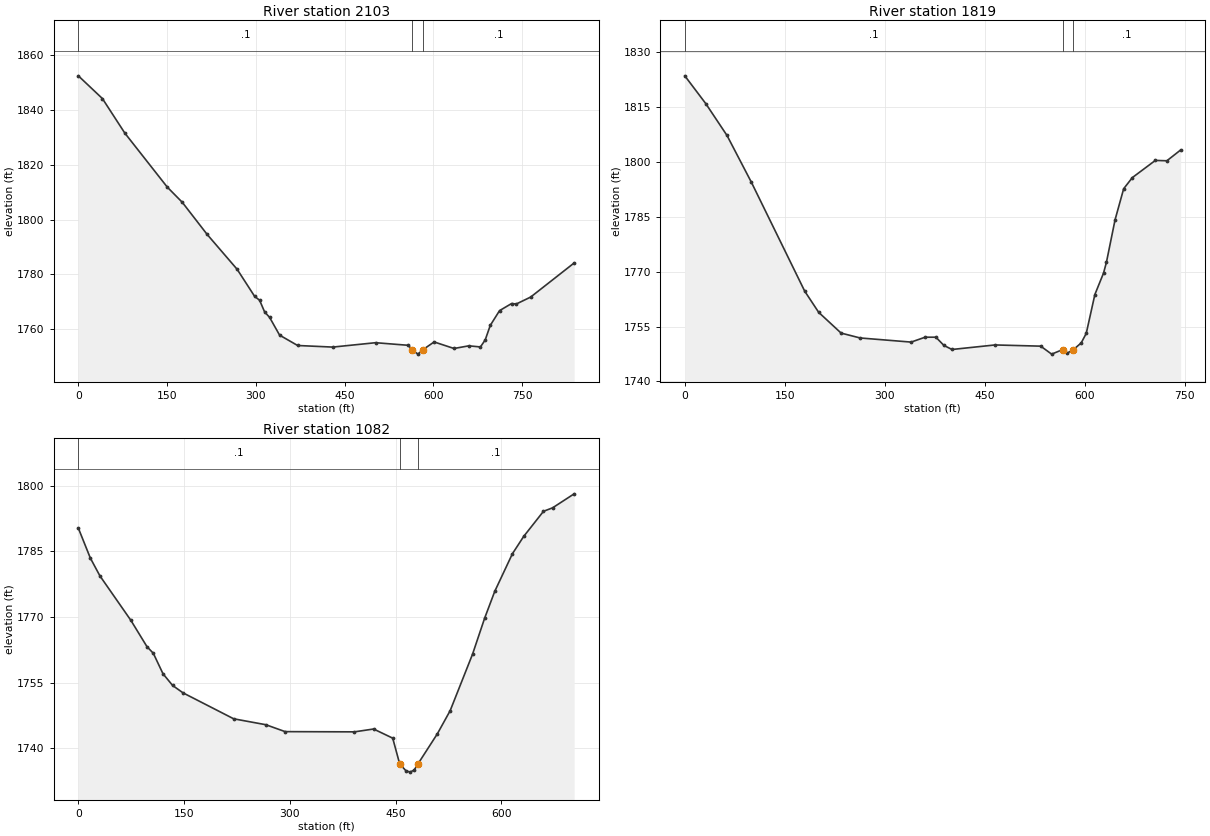
Type RM Length L Ch R = 1 ,2103    ,278.7,284.1,288.8
XS GIS Cut Line= 4
2264865.97679066716918.6299601152264707.41928688717391.786494136
2264731.55980876717500.5444326182264700.20504723 717726.09820176
#Sta/Elev= 30
       0  1852.5    40.7  1844.2    78.6 1831.59   150.3 1811.89   175.7 1806.33
   217.8 1794.59   268.5 1781.86     298    1772   306.4 1770.58   314.9  1766.3
   323.3 1764.33   340.2 1757.84   370.7 1754.06     430 1753.48   502.5 1755.08
   557.8 1754.13   564.5 1752.38   574.2 1750.91   582.4 1752.53   601.4 1755.36
     635 1752.97   660.1 1753.94   679.7 1753.53   687.8 1756.12   696.3  1761.4
     712 1766.79   732.2 1769.36   740.3 1769.21   764.5 1771.73   838.1 1784.19
#Mann= 3 ,-1,0
       0      .1       0   564.5    .045       0   582.4      .1       0
Bank Sta=564.5,582.4
XS Rating Curve= 0 ,0
Exp/Cntr(USF)=0,0
Exp/Cntr=0.3,0.1

Type RM Length L Ch R = 1 ,1819    ,749.2,736.5,721.5
XS GIS Cut Line= 4
2264592.62657062716894.0317796642264482.92183772717235.380706919
2264459.40397058717421.4845226942264384.85783877 717604.24358833
#Sta/Elev= 30
       0 1823.55    31.5 1815.94    63.3 1807.24    99.9 1794.43   179.8 1764.67
   200.8 1758.87   234.4  1753.2   262.9 1751.87   339.4 1750.74   360.4 1752.08
   376.5 1752.08   388.6 1749.82   400.7 1748.72   465.2 1749.96   533.7 1749.63
   550.1 1747.45   566.8  1748.7   572.9 1747.67  582.771748.691   594.4 1750.51
     602 1753.13   614.9 1763.74   627.9 1769.61   632.2 1772.52   645.2 1784.19
   658.1 1792.68   671.1 1795.72   705.6 1800.42   722.9 1800.32   743.5 1803.27
#Mann= 3 ,-1,0
       0      .1       0   566.8    .045       0  582.77      .1       0
Bank Sta=566.8,582.77
XS Rating Curve= 0 ,0
Exp/Cntr(USF)=0,0
Exp/Cntr=0.3,0.1

Type RM Length L Ch R = 1 ,1082    ,382.1,384,385.2
XS GIS Cut Line= 4
2263816.00798088717243.7881112862263960.88496159717508.740995248
2264215.03435103717643.3159233162264320.52310377717686.152654505
#Sta/Elev= 30
       0  1790.3      17 1783.47    30.6 1779.39    74.5 1769.24    97.3 1763.24
   106.4  1761.7   120.1 1757.03   133.8 1754.35   148.5 1752.67   220.4 1746.74
     266 1745.39   293.4 1743.81   391.7 1743.76   418.9 1744.41     446 1742.32
  455.871736.441   464.5 1734.92   470.5 1734.56   476.4 1735.03  481.831736.442
   509.4 1743.33   527.5  1748.6   559.2 1761.48   576.4 1769.72   590.8 1775.87
   615.8 1784.44   631.8  1788.4   659.9 1794.14   672.8 1794.93   703.4 1798.13
#Mann= 3 ,-1,0
       0      .1       0  455.87    .045       0  481.83      .1       0
Bank Sta=455.87,481.83
XS Rating Curve= 0 ,0
Exp/Cntr(USF)=0,0
Exp/Cntr=0.3,0.1