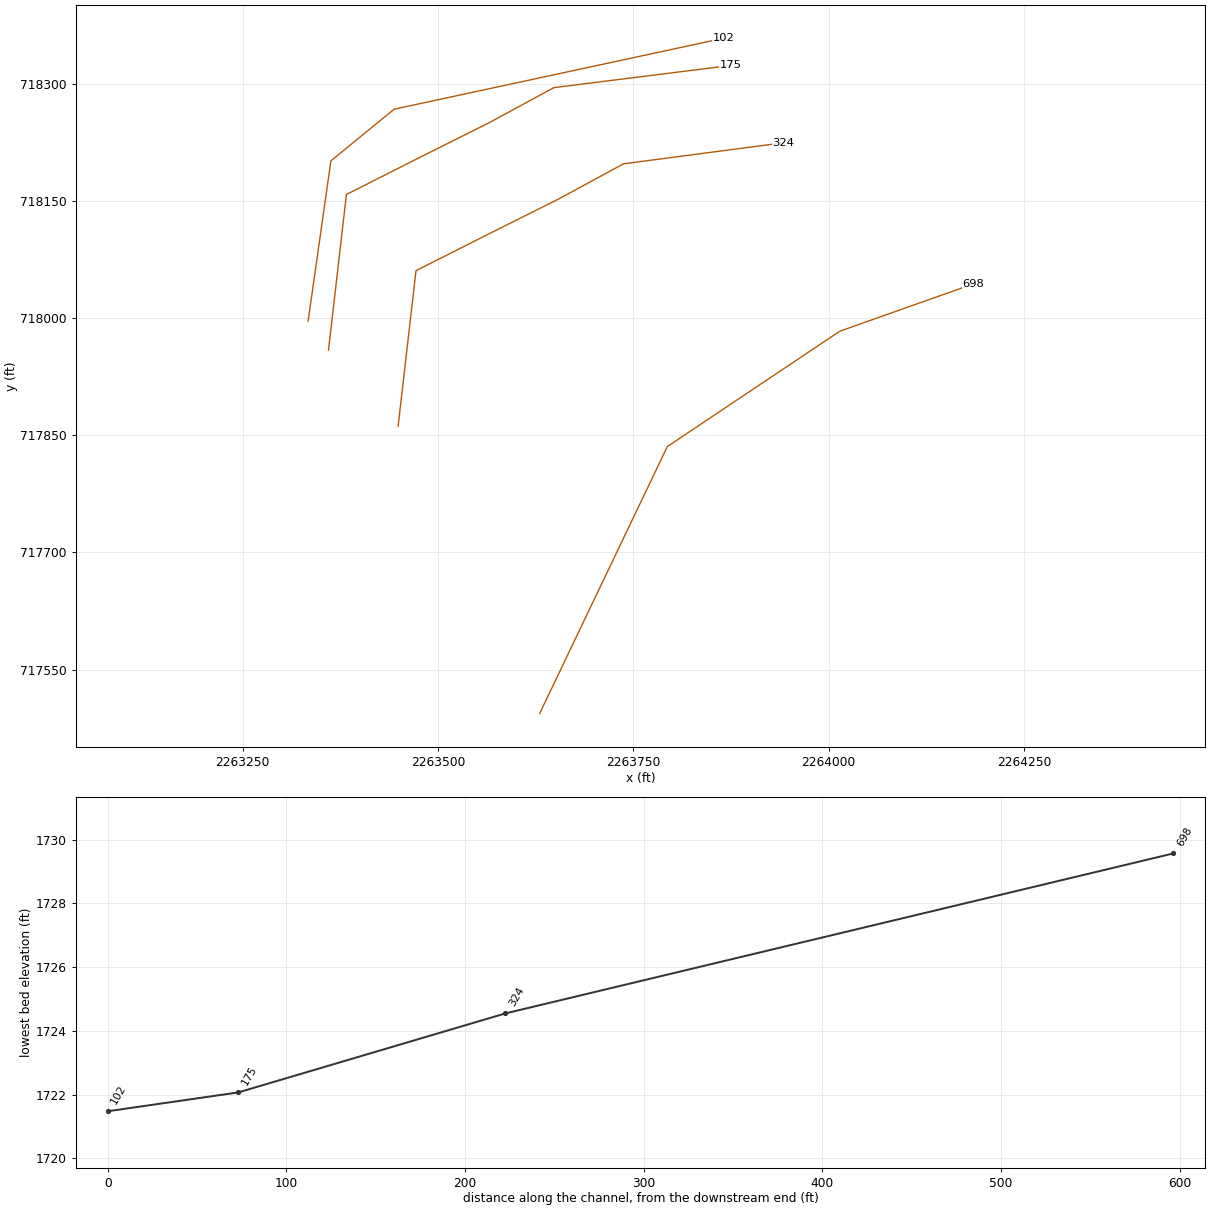
HEC-RAS study BEAVCK2.prj: BEAVCK2

--- BEAVCK2.g01 (geometry) --- (continued)

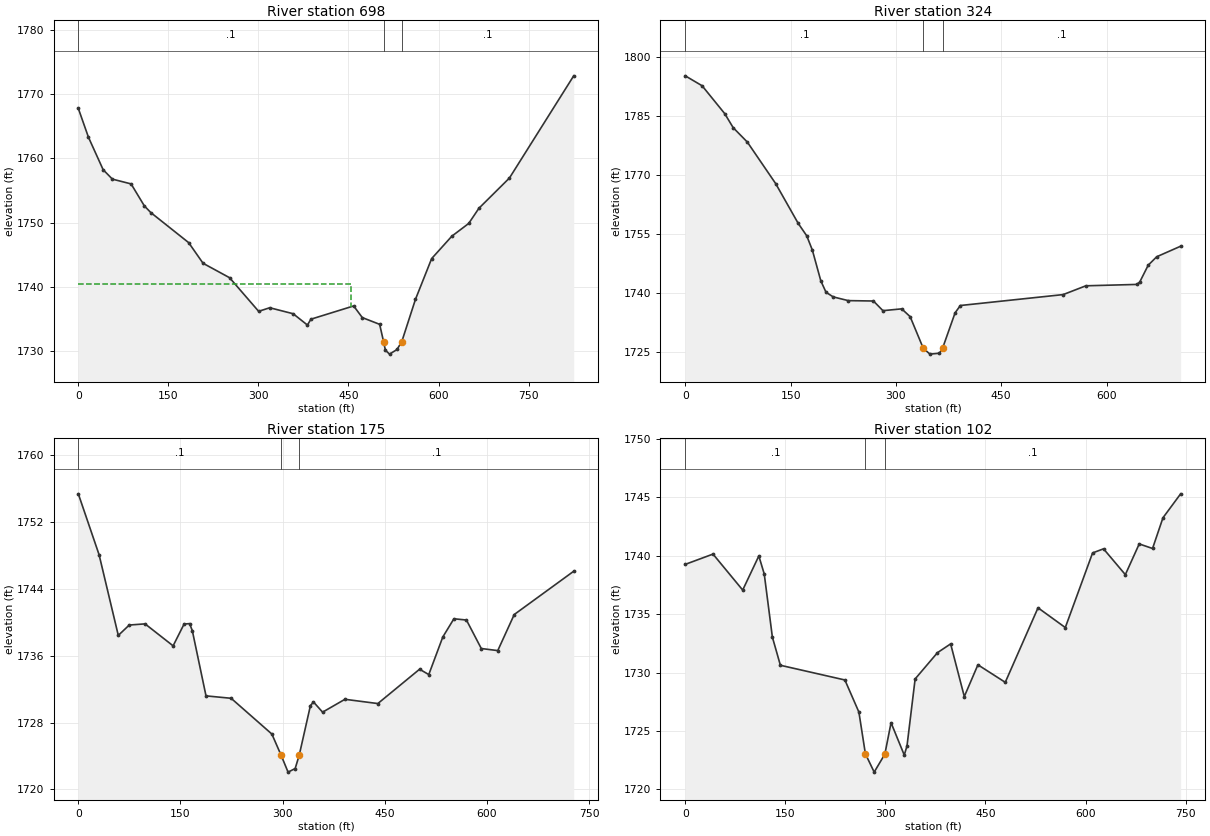
Type RM Length L Ch R = 1 ,698     ,375.8,373.9,374
XS GIS Cut Line= 4
2263630.32435165 717493.912650912263793.61533468717835.374418822
2264014.29147179717982.9867386592264184.99222507718043.489251345
#Sta/Elev= 30
       0 1767.77    16.9 1763.28    41.4 1758.23    56.8 1756.77    87.9 1756.03
     110 1752.61   120.8 1751.57   183.8  1746.9   207.8 1743.69   251.9 1741.45
   300.4 1736.22   318.8 1736.78   357.8 1735.85   381.6 1734.09   387.4    1735
   458.6 1737.06     473 1735.25   501.9  1734.2  508.391731.526   511.5 1730.17
   518.4 1729.57   530.8 1730.29   538.81731.525   561.6  1738.1   588.5 1744.42
   622.2 1747.91   650.2 1749.88   667.2 1752.24   718.1 1756.95   825.1 1772.83
#Mann= 3 ,-1,0
       0      .1       0  508.39    .045       0   538.8      .1       0
#XS Ineff= 2 , 0
          454.77 1740.51
Permanent Ineff=
       F       F
Bank Sta=508.39,538.8
XS Rating Curve= 0 ,0
Exp/Cntr(USF)=0,0
Exp/Cntr=0.3,0.1

Type RM Length L Ch R = 1 ,324     ,149.1,149.6,149.6
XS GIS Cut Line= 6
2263449.05474311717861.3313402342263471.96458285718060.517168909
2263564.12879321718107.0947805962263655.30199056718152.681379268
2263737.55607077718197.2769649252263942.00611658718224.222282851
#Sta/Elev= 30
       0 1795.18      24 1792.66    56.2 1785.59    68.3 1782.01    88.4 1778.37
   128.7 1767.85   160.9 1757.72     173 1754.58     181 1750.96   193.1 1743.13
   200.5 1740.24   210.8 1739.07   232.1 1738.13     268 1738.03   281.5 1735.58
   308.3 1736.04   320.3 1734.05  338.99 1726.02   348.5 1724.55     362 1724.78
   366.4 1726.02   384.3 1735.04   391.8 1736.89   538.2 1739.66   570.5 1741.89
   643.1 1742.24   647.2 1742.83   659.3 1747.12   671.4 1749.26   705.5 1751.94
#Mann= 3 ,-1,0
       0      .1       0  338.99    .045       0   366.4      .1       0
Bank Sta=338.99,366.4
XS Rating Curve= 0 ,0
Exp/Cntr(USF)=0,0
Exp/Cntr=0.3,0.1

Type RM Length L Ch R = 1 ,175     ,70.1,73,74.8
XS GIS Cut Line= 6
2263359.97684459717958.8618860672263382.88668433718158.047714742
2263475.05089469718204.6253264292263566.22409203718250.211925101
2263648.47817224718294.8075107592263874.89107128 718323.18761149
#Sta/Elev= 30
       0 1755.39    30.5  1748.1    58.7 1738.44    74.8 1739.68      98 1739.82
   139.2 1737.19   155.3  1739.8   163.4 1739.85   167.4 1739.01   187.5  1731.2
   224.4 1730.91   284.2 1726.63  297.831724.081     308 1722.07   318.4  1722.5
  324.331724.081   340.8 1730.03   345.3 1730.47   358.7 1729.25   391.5 1730.79
   439.8 1730.28   501.1 1734.39   514.6 1733.75   535.2 1738.25   551.5 1740.43
   569.9 1740.28   591.7 1736.87   615.9 1736.62   640.1 1740.94   727.4 1746.12
#Mann= 3 ,-1,0
       0      .1       0  297.83    .045       0  324.33      .1       0
Bank Sta=297.83,324.33
XS Rating Curve= 0 ,0
Exp/Cntr(USF)=0,0
Exp/Cntr=0.3,0.1

Type RM Length L Ch R = 1 ,102     ,,,
XS GIS Cut Line= 4
2263333.87866146717995.9577607372263363.04991379718201.100078752
2263443.97301123718267.2116688832263865.17976693718357.902938212
#Sta/Elev= 30
       0 1739.27    41.6 1740.15    86.1 1737.07   110.3 1739.99   118.4 1738.45
   130.6 1733.04   142.6 1730.63   239.3 1729.37   260.3 1726.62  270.011723.055
   283.2 1721.48   299.2 1723.02   308.5 1725.71   328.3 1722.94   332.4 1723.72
   344.6 1729.46   378.1 1731.71   397.8 1732.46   418.3 1727.95   438.7 1730.67
   479.7 1729.17   528.8 1735.55   569.7 1733.86   610.6 1740.25     627  1740.6
   659.7 1738.39   680.5 1741.02   700.5 1740.63   716.1 1743.26   742.6 1745.31
#Mann= 3 ,-1,0
       0      .1       0  270.01    .045       0   299.2      .1       0
Bank Sta=270.01,299.2
XS Rating Curve= 0 ,0
Exp/Cntr(USF)=0,0
Exp/Cntr=0.3,0.1
LCMann Table=0

Chan Stop Cuts=-1
Use User Specified Reach Order=0
Composite Channel Slope=5